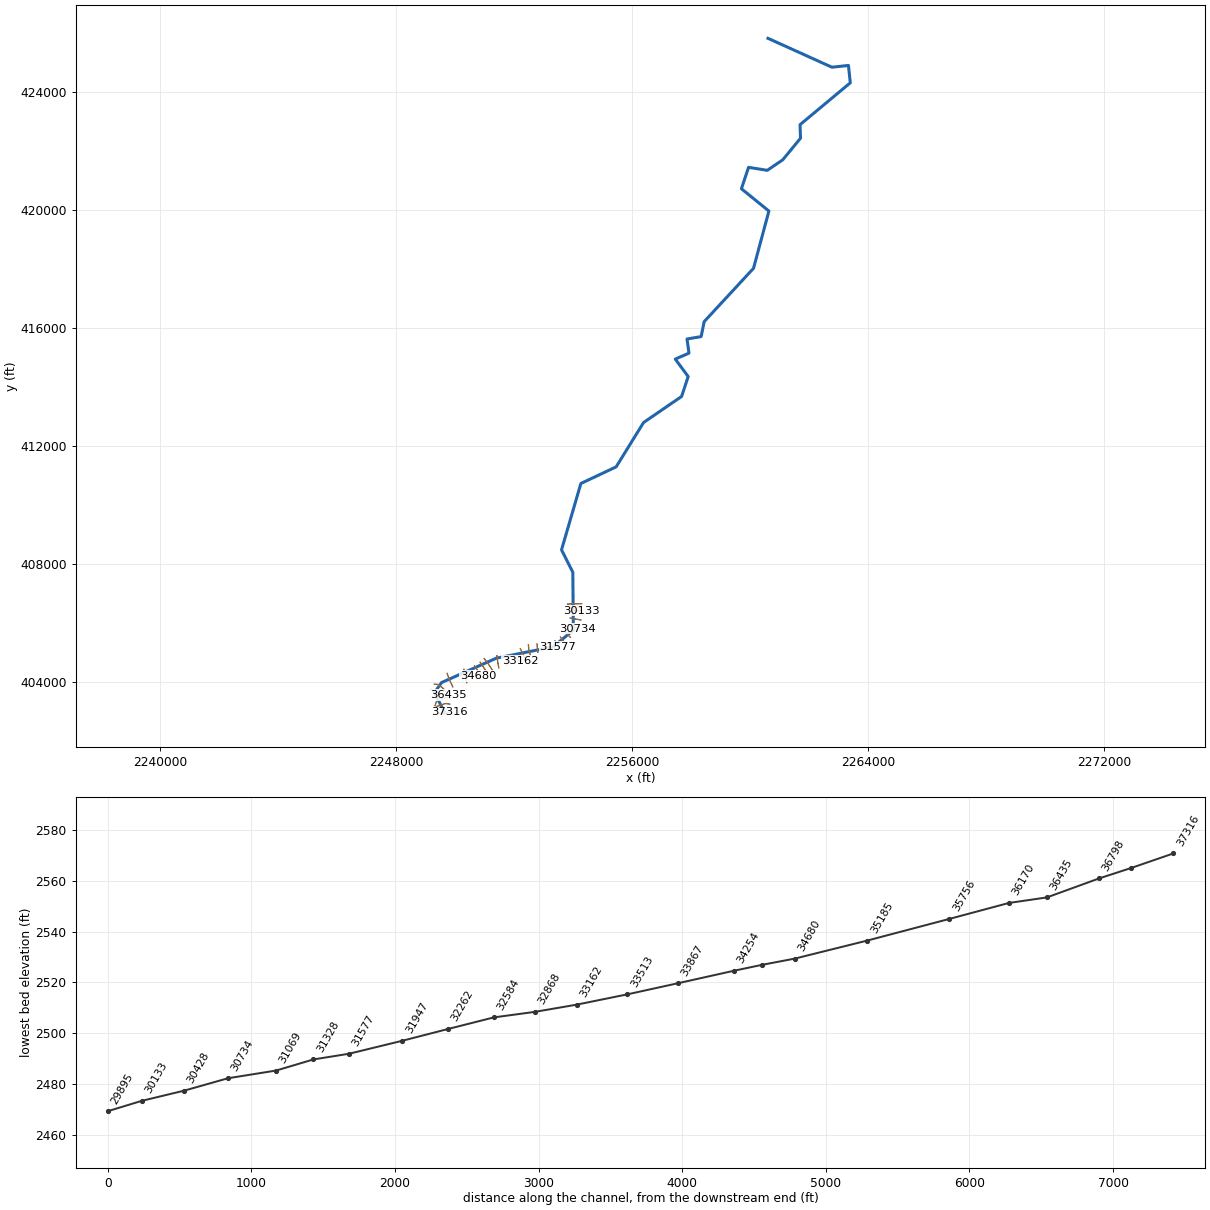
--- DOUTHTCK.prj (project) ---

Proj Title=DOUTHTCK
Current Plan=p01
Default Exp/Contr=0,0
English Units
Geom File=g01
Flow File=f01
Plan File=p01
Background Map Layer=FWY
Background Map Layer=Inundation Boundary (FWY Value_0)
BEGIN DESCRIPTION:
----------MODEL BY WOOD PLC 2021----------
Stream Name:Douthat Creek
Flood Zone:  Detailed from XS 0- 26206 and exnhanced approximate from 26206-37316
Pocahontas County, WV
HEC-RAS Version: RAS 6.1
Vertical Datum: NAVD88
Projection: NAD 1983 StatePlane West Virginia S FIPS 4702 (US Feet)
Terrain: 1-meter LIDAR (FEMA Region III 3DEP collected 2016-2018)
Land Use: 2019 NLCD
Hydrologic Method:
WV SIR2010-5033 regression equations
Model Notes:
Coincident peaks with Knapp Creek
Zone AE- 0-26482
Zone A- 26482-37317
END DESCRIPTION:
DSS File=dss
DSS Export Rating Curves= 0
DSS Export Rating Curve Sorted= 0
DSS Export Volume Flow Curves= 0
DXF OffsetX= 0
DXF OffsetY= 0
DXF ScaleX= 0
DXF ScaleY= 0

--- DOUTHTCK.p01 (plan) ---

Plan Title=Floodplain
Program Version=6.10
Short Identifier=Floodplain
Geom File=g01
Flow File=f01
Subcritical Flow
K Sum by GR= 0
Std Step Tol= 0.01
Critical Tol= 0.01
Num of Std Step Trials= 20
Max Error Tol= 0.3
Flow Tol Ratio= 0.001
Split Flow NTrial= 30
Split Flow Tol= 0.02
Split Flow Ratio= 0.02
Log Output Level= 0
Friction Slope Method= 1
Unsteady Friction Slope Method= 2
Unsteady Bridges Friction Slope Method= 1
Parabolic Critical Depth
Global Vel Dist= 0 , 0 , 0
Global Log Level= 0
CheckData=True
Encroach Param=-1 ,0,0, 2
Encroach River=DOUTHTCK
Encroach Reach=Main
Encroach Node=26473
       1  367.44  476.32
Encroach Node=26198
       1   502.4   621.5
Encroach Node=25588
       1   272.8   410.5
Encroach Node=25219
       1  298.78  394.16
Encroach Node=24691
       1  471.24  559.03
Encroach Node=24438
       1  498.07  544.04
Encroach Node=24163
       1  688.68   761.1
Encroach Node=24040
       1  604.48   681.6
Encroach Node=23612
       1  671.25   744.3
Encroach Node=23450
       1  585.89   632.1
Encroach Node=23115
       1   690.2  764.88
Encroach Node=22685
       1  549.57  617.76
Encroach Node=22386
       1  369.78   430.7
Encroach Node=22074
       1  345.57   448.9
Encroach Node=21743
       1   403.9     525
Encroach Node=21079
       1   607.2   807.9
Encroach Node=20375
       1     808     889
Encroach Node=19779
       1  787.99   992.6
Encroach Node=18989
       1   403.6  494.65
Encroach Node=18835
       1   299.7  440.68
Encroach Node=18596
       1  264.07   410.2
Encroach Node=17966
       1  281.39  488.75
Encroach Node=17417
       1   454.3  666.51
Encroach Node=16651
       1   413.8  555.91
Encroach Node=16116
       1  303.44  393.46
Encroach Node=15619
       1     383   492.2
Encroach Node=14983
       1  330.35   457.8
Encroach Node=14648
       1  220.87   343.2
Encroach Node=14166
       1   362.7   470.9
Encroach Node=13797
       1  497.28  678.05
Encroach Node=13284
       1  493.18  640.89
Encroach Node=12664
       1  926.36  1134.7
Encroach Node=11746
       1  849.93 1043.05
Encroach Node=11210
       1   781.2  1049.1
Encroach Node=11016
       1     937  1080.1
Encroach Node=10316
       1   337.7  551.93
Encroach Node=10020
       1  302.65  530.84
Encroach Node=9666
       1   380.1   569.5
Encroach Node=9427
       1   391.9  538.58
Encroach Node=9254
       1  325.53   519.4
Encroach Node=8825
       1   173.3   378.4
Encroach Node=8246
       1  384.65     630
Encroach Node=7941
       1   512.4   657.5
Encroach Node=7742
       1    1076    1237
Encroach Node=7618
       1     995    1157
Encroach Node=7159
       1  611.85   844.7
Encroach Node=6975
       1  381.05  623.48
Encroach Node=6882
       1  300.49     537
Encroach Node=6835
       1  287.22  516.27
Encroach Node=6656
       1  225.03   516.3
Encroach Node=6481
       1  258.28   557.6
Encroach Node=5960
       1   262.8  456.75
Encroach Node=5485
       1   216.8  430.63
Encroach Node=5027
       1   233.4   556.4
Encroach Node=4614
       1     207     574
Encroach Node=4409
       1   328.6   690.4
Encroach Node=3619
       1   666.4  886.28
Encroach Node=3440
       1   787.1  1021.7
Encroach Node=3078
       1  604.88     973
Encroach Node=2426
       1   284.9  404.59
Encroach Node=2174
       1  162.49  341.46
Encroach Node=1833
       1  174.44  568.04
Encroach Node=1792
       1  181.19  574.79
Encroach Node=1753
       1  169.74   479.8
Encroach Node=1704
       1  150.22  415.19
Encroach Node=1689
       1     134  414.09
Encroach Node=1322
       1    89.6  546.98
Encroach Node=774
       1  378.37  613.79
Encroach Node=523
       1  505.28   740.7
Encroach Node=233
       1  446.07   558.1
Encroach Node=0
       1  518.22  686.92
Computation Interval=0.1SEC
Output Interval=1SEC
Instantaneous Interval=Max Profile
Mapping Interval=1HOUR
Computation Time Step Use Courant=        0
Computation Time Step Use Time Series=    0
Computation Time Step Count To Double=0
Computation Time Step Max Doubling=0
Computation Time Step Max Halving=0
Computation Time Step Residence Courant=0
Run HTab= 0
Run UNet= 0
Run Sediment= 0
Run PostProcess= 0
Run WQNet= 0
Run RASMapper=-1
UNET Theta= 0
UNET Theta Warmup= 0
UNET ZTol= 0
UNET ZSATol= 0
UNET MxIter= 0
UNET Max Iter WO Improvement= 0
UNET MaxInSteps= 0
UNET DtIC= 0
UNET DtMin= 0
UNET MaxCRTS= 0
UNET WFStab= 0
UNET SFStab= 0
UNET WFX= 1
UNET SFX= 1
UNET Gravity=32.174
UNET 1D Methodology=Finite Difference
UNET DSS MLevel= 1
UNET Pardiso=0
UNET DZMax Abort= 0
UNET Use Existing IB Tables= 0
UNET Froude Reduction=False
UNET Froude Limit= 0
UNET Froude Power= 0
UNET D1 Cores= 0
UNET WindReference=Eulerian
UNET WindDragFormulation=Hsu (1988)
UNET D2 Coriolis=0
UNET D2 Cores= 0
UNET D2 Theta= 1
UNET D2 Theta Warmup= 1
UNET D2 Z Tol= 0.01
UNET D2 Volume Tol= 0.01
UNET D2 Max Iterations= 20
UNET D2 Equation= 0
UNET D2 RampUpFraction=0.1
UNET D2 TimeSlices= 1
UNET D2 Turbulence Formulation=Non-Conservative (original)
UNET D2 Eddy Viscosity=0.3
UNET D2 Transverse Eddy Viscosity=0.1
UNET D2 Smagorinsky Mixing=0
UNET D2 BCVolumeCheck=0
UNET D2 Cores=0
UNET D2 SolverType=PARDISO (Direct)
UNET D2 Minimum Iterations= 2147483647
UNET D2 Maximum Iterations= 2147483647
UNET D2 Restart Number= 10
UNET D2 Relaxation Coeff=1.3
UNET D2 SOR Precondition Iterations= 10
UNET D2 ILUT Maximum Fill= 8
UNET D2 ILUT Tolerance=1E-08
UNET D1D2 MaxIter= 0
UNET D1D2 ZTol=0.01
UNET D1D2 QTol=0.1
UNET D1D2 MinQTol=1
DSS File=dss
Write IC File= 0
Write IC File at Fixed DateTime=0
Write IC File at Sim End=0
Echo Input=False
Echo Parameters=False
Echo Output=False
Write Detailed= 0
HDF Write Warmup=0
HDF Write Time Slices=0
HDF Flush=0
HDF Compression= 1
HDF Chunk Size= 1
HDF Spatial Parts= 1
HDF Use Max Rows=0
HDF Fixed Rows= 1
Calibration Method= 0
Calibration Iterations= 20
Calibration Max Change=0.05
Calibration Tolerance=0.2
Calibration Maximum=1.5
Calibration Minimum=0.5
Calibration Optimization Method= 1
WQ AD Non Conservative
WQ ULTIMATE=-1
WQ Max Comp Step=1HOUR
WQ Output Interval=15MIN
WQ Output Selected Increments= 0
WQ Output face flow=0
WQ Output face velocity=0
WQ Output face area=0
WQ Output face dispersion=0
WQ Output cell volume=0
WQ Output cell surface area=0
WQ Output cell continuity=0
WQ Output cumulative cell continuity=0
WQ Output face conc=0
WQ Output face dconc_dx=0
WQ Output face courant=0
WQ Output face peclet=0
WQ Output face adv mass=0
WQ Output face disp mass=0
WQ Output cell mass=0
WQ Output cell source sink temp=0
WQ Output nsm pathways=0
WQ Output nsm derived pathways=0
WQ Create Restart=0
WQ Fixed Restart=0
WQ System Summary=0
WQ Write To DSS=0
Sorting and Armoring Iterations= 10
XS Update Threshold= 0.02
Bed Roughness Predictor= 0
Hydraulics Update Threshold= 0.02
Energy Slope Method= 1
Volume Change Method= 1
Sediment Retention Method= 0
Sediment TS Multiplier= 1
Warm Up Method= 0
XS Weighting Method= 0
Number of US Weighted Cross Sections= 1
Number of DS Weighted Cross Sections= 1
Upstream XS Weight=0
Main XS Weight=1
Downstream XS Weight=0
Number of DS XS's Weighted with US Boundary= 1
Upstream Boundary Weight= 1
Weight of XSs Associated with US Boundary= 0
Number of US XS's Weighted with DS Boundary= 1
Downstream Boundary Weight= 0.5
Weight of XSs Associated with DS Boundary= 0.5
Percentile Method= 0
Sediment Output Level= 3
Mass or Volume Output= 0
Output Increment Type= 1
Profile and TS Output Increment= 1
Transport Output Increment 1
XS Output Flag= 0
XS Output Increment= 10
Read HDF5 Sediment Hotstart= 0
Sediment Hotstart Type= 0
Write Gradation File= 0
Read Gradation Hotstart= 0
Write HDF5 File= 1
Write Binary Output= 1
Write DSS Sediment File= 0
DSS Sediment Output Type= 1
SV Curve= 0
Specific Gage Flag= 0
Subcell Erosion Methods= 0
Subcell Deposition Methods= 0
Advection Scheme= 1
Matrix Solver= 0
Implicit Weighting Factor= 1
Maximum Outer Loop Convergence Iterations= 5
Convergence Maximum Absolute= 0.001
Convergence RMSE= 0.0001
Grain Fractions Max Abs Error= 0.001
Max Subgrid Regions= 1
Max Subgrid Length Scale= 3.402823E+38
Initial Layer Thickness= 3.402823E+38
Min Layer Thickness= 3.402823E+38
Max Layer Thickness= 3.402823E+38
Number of Layers= 5

--- DOUTHTCK.f01 (steady flow) ---

Flow Title=Flow
Program Version=6.10
Number of Profiles= 7
Profile Names=01pct,FWY,10pct,04pct,02pct,0_2pct,01plus
River Rch & RM=DOUTHTCK,Main            ,37316
     892     892     480     633     758    1240    1320
River Rch & RM=DOUTHTCK,Main            ,34254
    1010    1010     547     720     861    1400    1500
River Rch & RM=DOUTHTCK,Main            ,32868
    1130    1130     611     802     959    1550    1660
River Rch & RM=DOUTHTCK,Main            ,27363
    1440    1440     786    1030    1220    1970    2120
River Rch & RM=DOUTHTCK,Main            ,24040
    1710    1710     941    1230    1460    2330    2520
River Rch & RM=DOUTHTCK,Main            ,18989
    1920    1920    1060    1380    1640    2620    2840
River Rch & RM=DOUTHTCK,Main            ,17966
    2140    2140    1190    1540    1830    2910    3160
River Rch & RM=DOUTHTCK,Main            ,11746
    4540    4540    2600    3320    3910    6090    6710
River Rch & RM=DOUTHTCK,Main            ,774
   11600   11600    6670    8500    9990   16300   17000
Boundary for River Rch & Prof#=DOUTHTCK,Main            , 1
Up Type= 0
Dn Type= 1
Dn Known WS=2312.2
Boundary for River Rch & Prof#=DOUTHTCK,Main            , 2
Up Type= 0
Dn Type= 1
Dn Known WS=2312.9
Boundary for River Rch & Prof#=DOUTHTCK,Main            , 3
Up Type= 0
Dn Type= 1
Dn Known WS=2308.7
Boundary for River Rch & Prof#=DOUTHTCK,Main            , 4
Up Type= 0
Dn Type= 1
Dn Known WS=2310
Boundary for River Rch & Prof#=DOUTHTCK,Main            , 5
Up Type= 0
Dn Type= 1
Dn Known WS=2311.1
Boundary for River Rch & Prof#=DOUTHTCK,Main            , 6
Up Type= 0
Dn Type= 1
Dn Known WS=2315.5
Boundary for River Rch & Prof#=DOUTHTCK,Main            , 7
Up Type= 0
Dn Type= 1
Dn Known WS=2316
DSS Import GetInterval= 0
DSS Import GetPeak= 0
DSS Import FillOption= 0

--- DOUTHTCK.g01 (geometry) ---

Geom Title=Geometry
Program Version=6.10

River Reach=DOUTHTCK        ,Main
Reach XY= 30
2249647.52095672402946.6918724782249301.59710789 403631.86799556
 2249540.1100823  403972.88240542251399.81404005404801.371890143
2253323.05297571405184.7310315672254009.58506723405753.202991724
2253991.35683132407715.9709435342253608.45594822408475.469856888
2254264.21415114410726.6169293972255460.02803247411291.517046317
2256390.04192047  412795.79586192257678.48914672413679.900064811
2257902.67898706414354.6349358112257465.67395556414947.727909729
2257929.13959346415150.093704686 2257863.4644339415628.942195452
2258341.92712431415711.9189666512258444.70185314416219.322151303
2260117.36287789418027.1630238152260639.07312055419970.862876564
 2259706.7708513420727.8908900622259949.42423739421453.885829151
2260584.63294072421352.5628690572261108.78937273421709.276066393
2261710.88987455422441.1279491482261695.09003739422901.690020144
2263398.45900597424321.9709722252263336.24915664424910.663036317
2262775.52685289424851.0270007252260608.44096397425830.676616222

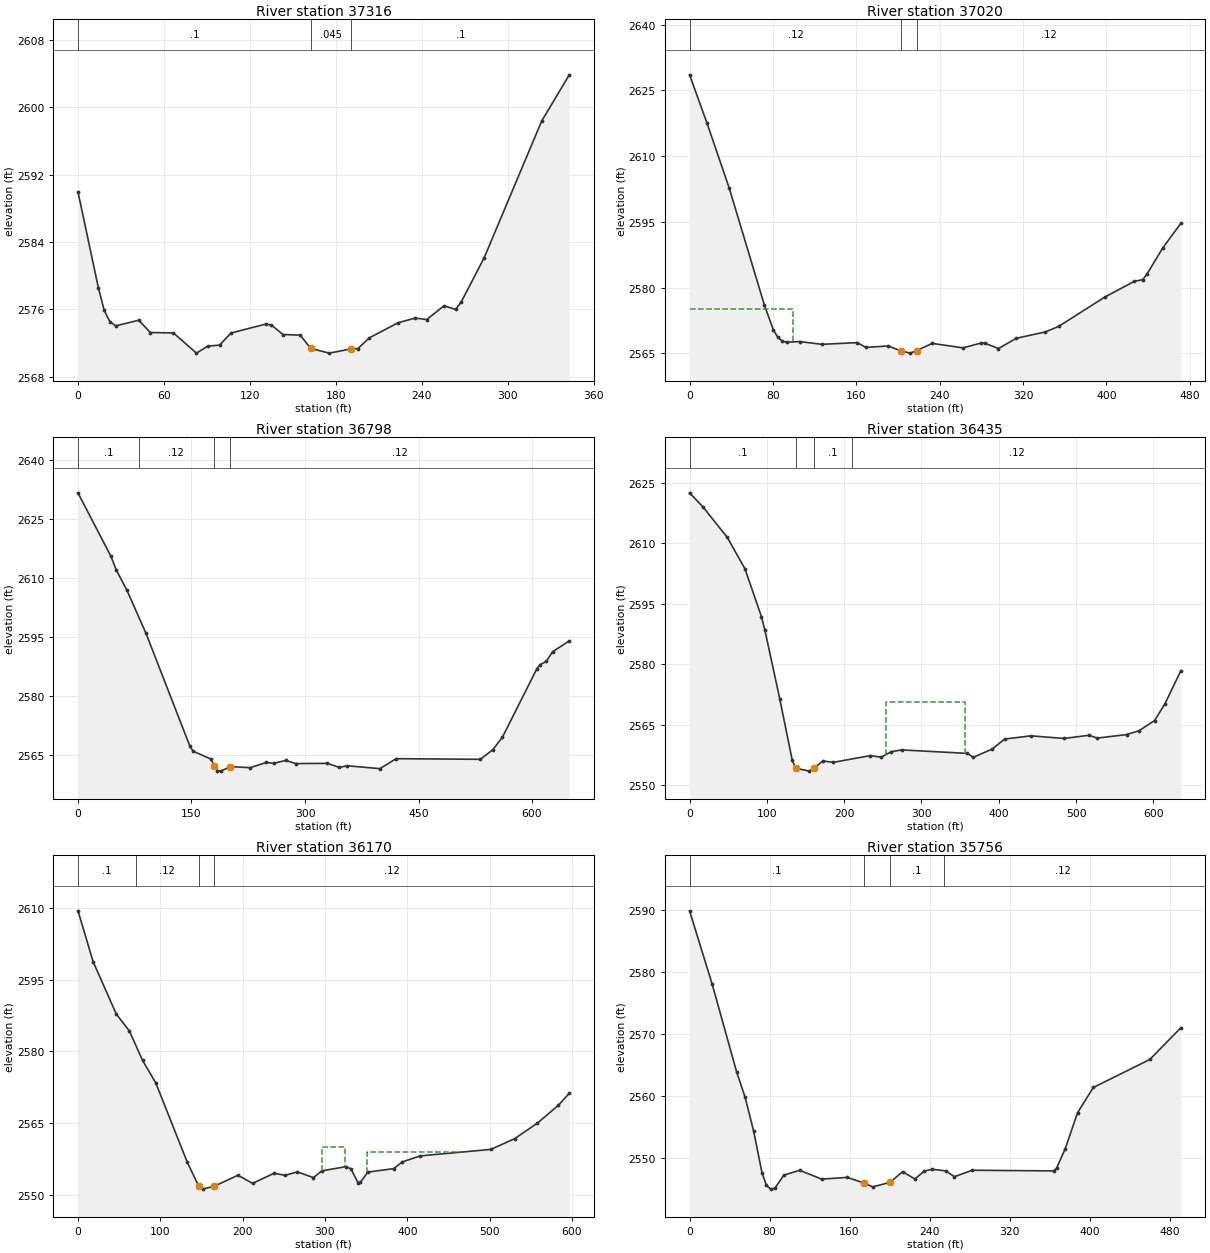
Type RM Length L Ch R = 1 ,37316   ,289.3,295.9,299.7
XS GIS Cut Line= 4
2249474.01699731402927.6346391952249653.81282173402948.128051424
2249800.12746043402956.8575969682249815.31435436402958.882516158
#Sta/Elev= 30
       0 2589.97    14.2  2578.6    18.3 2575.88    22.3 2574.53    26.3 2574.04
    42.4 2574.71    50.5 2573.25    66.6  2573.2    82.7  2570.8    90.7 2571.64
    98.8 2571.75   106.8 2573.19     131 2574.25     135 2574.14   143.1 2573.01
   155.1 2572.94   162.4 2571.37   175.3  2570.8   190.9 2571.31   195.3 2571.33
   203.4 2572.62   223.4 2574.41   235.4 2574.97   243.4 2574.79   255.5 2576.43
   263.6 2575.99   267.6 2576.92   283.5 2582.13   323.6 2598.37   342.9 2603.88
#Mann= 3 ,-1,0
       0      .1       0   162.4    .045       0   190.9      .1       0
Bank Sta=162.4,190.9
XS Rating Curve= 0 ,0
Exp/Cntr(USF)=0,0
Exp/Cntr=0.3,0.1

Type RM Length L Ch R = 1 ,37020   ,195.2,221.8,184.9
XS GIS Cut Line= 3
2249368.32055881403157.4449702022249671.24710333403263.347806377
2249820.35084536403241.656006437
#Sta/Elev= 30
       0 2628.52    16.8 2617.46      38 2602.73    71.9 2575.93    80.4 2570.36
    84.6  2568.7    88.8 2567.81    93.1 2567.51   105.8 2567.67     127 2567.04
   160.9 2567.42   169.3 2566.34   190.5 2566.66   203.2 2565.54   211.7 2565.03
   217.9 2565.59   232.9 2567.25   262.6 2566.23   279.5 2567.32   283.8 2567.26
   296.5 2566.08   313.7 2568.42   341.3 2569.85   354.2 2571.11   398.6 2577.82
   426.9  2581.4     435  2581.8   439.1 2583.07   454.2 2589.02   471.6 2594.65
#Mann= 3 ,-1,0
       0     .12       0   203.2    .045       0   217.9     .12       0
#XS Ineff= 2 , 0
           98.84  2575.2
Permanent Ineff=
       F       F
Bank Sta=203.2,217.9
XS Rating Curve= 0 ,0
Exp/Cntr(USF)=0,0
Exp/Cntr=0.3,0.1

Type RM Length L Ch R = 1 ,36798   ,351.5,363.1,264.8
XS GIS Cut Line= 4
2249322.34050446403193.1601855072249373.53064187 403345.24682564
2249717.02388276403477.3025424392249833.49999252403445.401442314
#Sta/Elev= 30
       0  2631.6    43.4 2615.54    50.7 2611.98    64.6 2606.89    89.9 2595.92
   147.7 2567.38     152 2566.02   176.2 2563.97  179.81 2562.14   184.1  2561.1
     189 2560.95  201.08  2562.1   227.6 2561.83     249 2563.16   258.4 2562.92
   274.7 2563.68   287.6 2562.87   329.6 2562.92   345.1 2561.91   356.1 2562.31
     399 2561.58   420.4 2564.11   531.7 2563.95   548.3 2566.41   560.8 2569.54
   606.4 2586.95   610.5 2587.97   618.8 2588.79   627.1 2591.24   649.2 2594.02
#Mann= 4 ,-1,0
       0      .1       0      80     .12       0  179.81    .045       0
  201.08     .12       0
Bank Sta=179.81,201.08
XS Rating Curve= 0 ,0
Exp/Cntr(USF)=0,0
Exp/Cntr=0.3,0.1

Type RM Length L Ch R = 1 ,36435   ,267.3,265.1,251.9
XS GIS Cut Line= 3
2249176.18895272403732.511343444 2249464.0407399403596.004310348
2249777.85853881403551.491147382
#Sta/Elev= 30
       0 2622.46    17.7 2618.88    48.7 2611.43    71.6 2603.65      93 2591.75
    97.4 2588.43   116.6 2571.45   132.8 2556.19   137.2 2554.18   154.9 2553.47
  160.81 2554.21   172.6 2555.98   185.9 2555.65   233.7 2557.31   247.9 2556.93
   260.7 2558.28   274.5 2558.73   359.1 2557.87   367.2 2556.91   391.4 2558.94
   407.6 2561.42   441.5 2562.22   484.4 2561.57   516.7 2562.36   527.3 2561.66
   565.2 2562.53   581.3 2563.48   601.5    2566   614.9 2570.16   635.5 2578.37
#Mann= 4 ,-1,0
       0      .1       0   137.2    .045       0  160.81      .1       0
     210     .12       0
#XS Ineff= 1 ,-1
  253.49  355.81 2570.49
Permanent Ineff=
       F
Bank Sta=137.2,160.81
XS Rating Curve= 0 ,0
Exp/Cntr(USF)=0,0
Exp/Cntr=0.3,0.1

Type RM Length L Ch R = 1 ,36170   ,425.8,414.3,366.1
XS GIS Cut Line= 4
2249297.77444807403916.2981004122249419.52757693403909.822109258
2249574.58176127403796.313543695 2249764.9534322403587.381840522
#Sta/Elev= 30
       0 2609.35    18.4 2598.74    46.5 2587.82    62.5 2584.26    78.5 2578.12
    94.5 2573.44   132.6 2556.96  146.51 2551.94   151.5 2551.28   165.8 2551.91
   194.4 2554.18     212 2552.48   238.1 2554.58   251.7 2554.16   266.5 2554.88
     286 2553.68   296.2  2555.1   325.9 2555.98   331.6  2555.5     340 2552.66
   342.9 2552.68   352.1 2554.84   383.3 2555.55   393.9 2556.96   415.7 2558.22
   501.5 2559.57   530.3  2561.8   558.1 2565.07   583.6 2568.79   596.7 2571.28
#Mann= 4 ,-1,0
       0      .1       0      70     .12       0  146.51    .045       0
   165.8     .12       0
#XS Ineff= 2 ,-1
  296.01  323.922560.093  350.83  465.452558.928
Permanent Ineff=
       F       F
Bank Sta=146.51,165.8
XS Rating Curve= 0 ,0
Exp/Cntr(USF)=0,0
Exp/Cntr=0.3,0.1

Type RM Length L Ch R = 1 ,35756   ,565.3,570.9,540.1
XS GIS Cut Line= 3
2249731.43051302404281.3422649472249815.05723894 404051.36876868
2249922.20398152403829.235277968
#Sta/Elev= 30
       0 2589.92    22.6 2578.09      47 2563.96    55.5 2559.85      64 2554.41
    72.5 2547.61    76.8 2545.64      81    2545    85.3 2545.16    94.3 2547.26
     110 2548.04   132.1 2546.62   157.7 2546.89   174.7 2545.97   183.2 2545.36
   200.5  2546.1     213 2547.81   225.4 2546.64   234.8 2547.93   242.8  2548.2
     256 2547.95   264.9 2547.01   282.7 2548.05     364 2547.94     367 2548.37
   375.7 2551.54     388 2557.34   403.8 2561.41   460.3 2565.93   491.3 2571.05
#Mann= 4 ,-1,0
       0      .1       0   174.7    .045       0   200.5      .1       0
  254.71     .12       0
Bank Sta=174.7,200.5
XS Rating Curve= 0 ,0
Exp/Cntr(USF)=0,0
Exp/Cntr=0.3,0.1

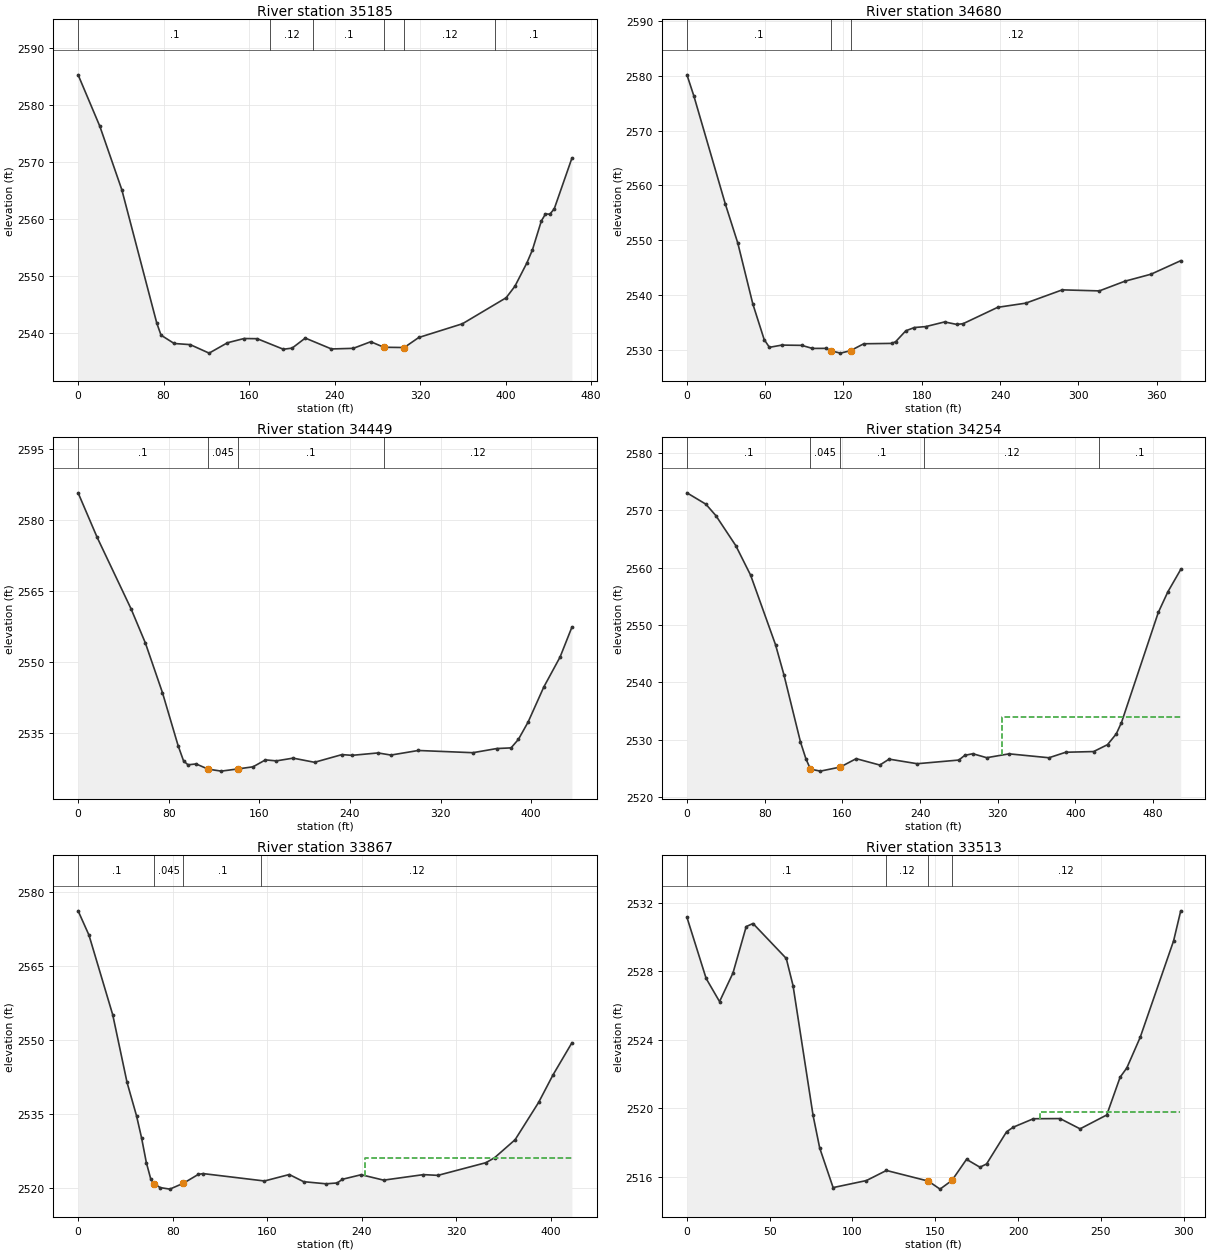
Type RM Length L Ch R = 1 ,35185   ,415.9,505.1,501.5
XS GIS Cut Line= 2
2250298.52424813404421.1556973362250393.91098238403969.048710357
#Sta/Elev= 30
       0 2585.27    20.4 2576.22    40.9 2565.13    73.6 2541.76    77.6 2539.63
    89.9 2538.17   104.9 2537.97   122.6 2536.48   139.8  2538.3   155.3 2539.04
   167.6 2539.01   192.1 2537.16   200.3 2537.36   212.6 2539.12   237.1 2537.21
   257.5 2537.32   273.9 2538.48   286.1 2537.51   305.2 2537.46   318.8 2539.22
   359.7 2541.63   400.6 2546.19   408.8 2548.21     420  2552.3   425.1 2554.54
   433.5 2559.64   437.4 2560.88   441.5 2560.84   445.6 2561.78   462.1 2570.65
#Mann= 6 ,-1,0
       0      .1       0     180     .12       0     220      .1       0
   286.1    .045       0   305.2     .12       0     390      .1       0
Bank Sta=286.1,305.2
XS Rating Curve= 0 ,0
Exp/Cntr(USF)=0,0
Exp/Cntr=0.3,0.1

Type RM Length L Ch R = 1 ,34680   ,231.1,230.8,229.9
XS GIS Cut Line= 3
2250658.47403172404537.5915101572250773.98568961404365.993266924
2250777.99187428 404194.39502369
#Sta/Elev= 30
       0 2580.22     5.3 2576.36    29.4 2556.63      39 2549.46    50.5 2538.35
    59.2 2531.85    63.2 2530.43    72.8 2530.84      88 2530.79    96.2 2530.23
   106.6 2530.24   110.32529.795   117.7 2529.37   125.4 2529.82   135.5 2531.08
   157.1 2531.15     160 2531.47   167.8 2533.46   174.4 2534.05   183.1 2534.22
   197.5 2535.07   206.9 2534.61   211.7 2534.75   238.2 2537.74   259.7  2538.5
   287.7 2540.93   316.1 2540.74   335.7 2542.51   355.7 2543.79   378.5 2546.26
#Mann= 3 ,-1,0
       0      .1       0   110.3    .045       0   125.4     .12       0
Bank Sta=110.3,125.4
XS Rating Curve= 0 ,0
Exp/Cntr(USF)=0,0
Exp/Cntr=0.3,0.1

Type RM Length L Ch R = 1 ,34449   ,192.2,194.8,203.9
XS GIS Cut Line= 2
2250850.10319828404662.4509322772251093.14506808404300.558917364
#Sta/Elev= 30
       0 2585.78    16.8 2576.36    46.8  2561.2    59.4 2553.99    74.5 2543.46
    88.3 2532.26    93.1 2529.04      97 2528.22   104.2  2528.4   114.8  2527.3
   126.4 2526.88   140.8 2527.34   154.4 2527.79   165.4 2529.26     175 2529.05
   189.8 2529.63   208.7 2528.75     233 2530.38   241.7 2530.22   264.7 2530.73
   276.2 2530.28   300.3 2531.25   348.5 2530.78   369.6 2531.66   382.2  2531.8
   388.7  2533.6   397.3 2537.29   411.1 2544.68   425.5 2551.04   435.9 2557.34
#Mann= 4 ,-1,0
       0      .1       0   114.8    .045       0   140.8      .1       0
     270     .12       0
Bank Sta=114.8,140.8
XS Rating Curve= 0 ,0
Exp/Cntr(USF)=0,0
Exp/Cntr=0.3,0.1

Type RM Length L Ch R = 1 ,34254   ,397.7,386.6,323.7
XS GIS Cut Line= 3
2250987.13806934 404784.409288032251108.65815544404632.835847309
2251281.13827764404370.195661231
#Sta/Elev= 30
       0 2573.04    19.5 2571.06    29.8 2569.07    50.3 2563.84    65.6 2558.68
    91.2 2546.59    99.8 2541.39   116.9 2529.65   122.5 2526.71   127.2 2524.91
   137.4 2524.56   157.9 2525.27   174.3 2526.73   198.6 2525.62   208.2 2526.65
   237.1 2525.85     280 2526.49   286.1 2527.31   294.4 2527.59   308.7  2526.9
   331.8 2527.57   372.8 2526.89   390.1 2527.85   418.8 2527.97   433.1 2529.17
   442.1 2531.04   447.5 2533.03   485.4  2552.2   495.3 2555.81   508.5 2559.69
#Mann= 5 ,-1,0
       0      .1       0   127.2    .045       0   157.9      .1       0
  244.27     .12       0  424.27      .1       0
#XS Ineff= 2 , 0
                          324.92         2534.05
Permanent Ineff=
       F       F
Bank Sta=127.2,157.9
XS Rating Curve= 0 ,0
Exp/Cntr(USF)=0,0
Exp/Cntr=0.3,0.1

Type RM Length L Ch R = 1 ,33867   ,355.4,354.4,313.5
XS GIS Cut Line= 3
2251418.33837484404886.3293602392251431.40505077404762.195938959
2251479.75175168404473.422401033
#Sta/Elev= 30
       0 2576.09     9.2 2571.16    29.3    2555    41.4  2541.3    49.4 2534.55
    53.7 2530.04    57.7 2525.07    61.5 2521.68    64.6 2520.69    69.5 2519.99
    77.6 2519.68    89.1 2520.88   101.7 2522.67   105.7 2522.83   157.6 2521.33
   178.6 2522.64   190.7 2521.19   209.7 2520.76   219.1 2520.93   223.6 2521.68
   239.4  2522.6   258.4  2521.5   292.1 2522.62   304.3 2522.47   344.9 2525.04
   352.2 2526.04   369.6  2529.7   389.5 2537.27   401.6 2542.82   417.6 2549.33
#Mann= 4 ,-1,0
       0      .1       0    64.6    .045       0    89.1      .1       0
  154.82     .12       0
#XS Ineff= 2 , 0
                          242.82         2525.92
Permanent Ineff=
       F       F
Bank Sta=64.6,89.1
XS Rating Curve= 0 ,0
Exp/Cntr(USF)=0,0
Exp/Cntr=0.3,0.1

Type RM Length L Ch R = 1 ,33513   ,255.3,351.3,368.9
XS GIS Cut Line= 2
 2251779.8730188404848.7224911822251741.73511915404552.842633048
#Sta/Elev= 30
       0 2531.15    11.6 2527.58    19.7 2526.23    27.8  2527.9    35.8 2530.61
    39.9 2530.79      60 2528.75    64.1 2527.16    76.2 2519.58    80.2 2517.68
    88.3 2515.37   108.4 2515.78   120.5 2516.37   145.8 2515.75   152.9 2515.28
   160.1 2515.79   168.9 2517.02     177 2516.56     181 2516.75   193.1 2518.63
   197.2  2518.9   209.3 2519.39   225.4  2519.4   237.5  2518.8   253.6 2519.61
   261.7 2521.82   265.7 2522.35   273.8 2524.14     294 2529.78   298.3 2531.53
#Mann= 4 ,-1,0
       0      .1       0     120     .12       0   145.8    .045       0
   160.1     .12       0
#XS Ineff= 1 ,-1
  213.46     298 2519.79
Permanent Ineff=
       F
Bank Sta=145.8,160.1
XS Rating Curve= 0 ,0
Exp/Cntr(USF)=0,0
Exp/Cntr=0.3,0.1

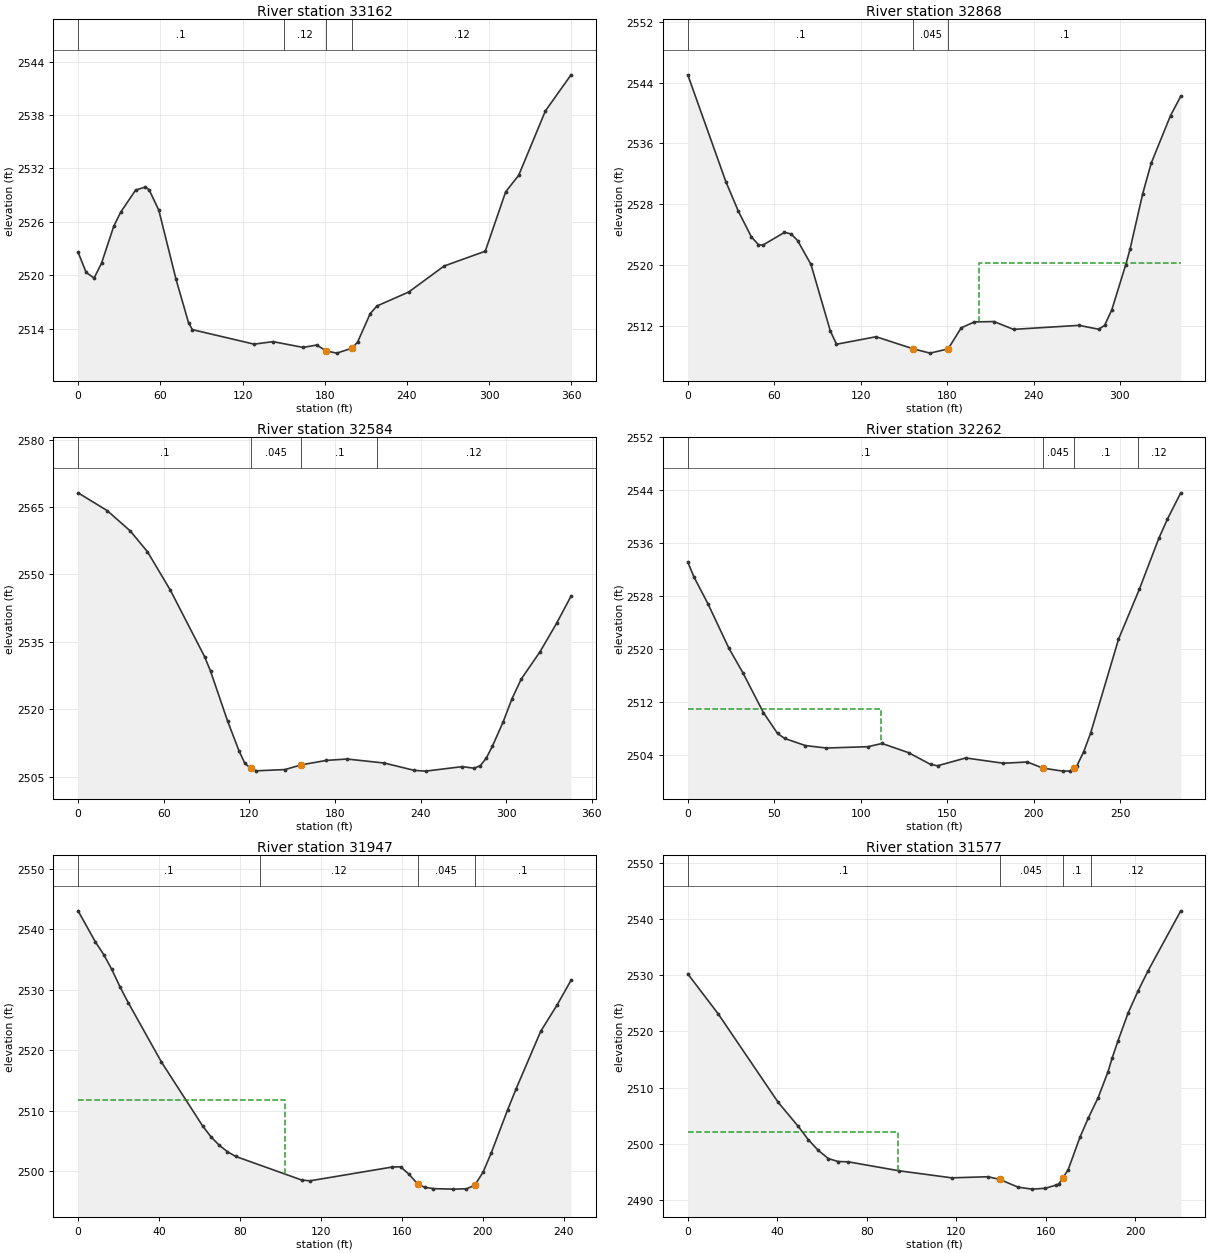
Type RM Length L Ch R = 1 ,33162   ,323.8,293.9,283.2
XS GIS Cut Line= 3
2251901.80538404404915.0760472722252113.48553401404766.115941736
2252194.49892474404706.009232485
#Sta/Elev= 30
       0 2522.59     5.9 2520.31    11.7 2519.67    17.2 2521.38      26 2525.48
    31.1 2527.08      42 2529.56      49  2529.9    51.8  2529.6    58.9 2527.31
    71.4 2519.58    80.6 2514.66    83.4 2513.88   128.4 2512.25   142.3 2512.53
   164.3 2511.88   174.1 2512.15   181.1 2511.49   188.8 2511.24     200  2511.8
     204  2512.5   213.2 2515.69   218.1 2516.54   241.3 2518.11   267.1 2521.03
   297.1 2522.69     312 2529.37   321.5 2531.22     341 2538.46   359.7 2542.51
#Mann= 4 ,-1,0
       0      .1       0     150     .12       0   181.1    .045       0
     200     .12       0
Bank Sta=181.1,200
XS Rating Curve= 0 ,0
Exp/Cntr(USF)=0,0
Exp/Cntr=0.3,0.1

Type RM Length L Ch R = 1 ,32868   ,269.9,283.6,228.3
XS GIS Cut Line= 2
2252211.53248684 405116.311660362252373.64832727404814.977697072
#Sta/Elev= 30
       0 2545.04    26.4 2530.98    35.1 2527.07    44.1  2523.7      49 2522.67
      52 2522.59    67.1 2524.28    71.7 2524.08    76.2 2523.21    85.5 2520.06
    98.9 2511.32   103.2 2509.54   130.7 2510.53   156.4 2508.94   168.2 2508.37
   180.7 2508.93   189.8  2511.7   198.9 2512.48   212.5 2512.53   226.1  2511.5
   271.5 2512.03   285.2 2511.52   289.3 2512.02   294.3 2514.06     304 2520.02
     307 2522.08   315.8 2529.39   321.7 2533.41   335.1 2539.68   342.2 2542.22
#Mann= 3 ,-1,0
       0      .1       0   156.4    .045       0   180.7      .1       0
#XS Ineff= 2 , 0
                          202.33         2520.26
Permanent Ineff=
       F       F
Bank Sta=156.4,180.7
XS Rating Curve= 0 ,0
Exp/Cntr(USF)=0,0
Exp/Cntr=0.3,0.1

Type RM Length L Ch R = 1 ,32584   ,299.6,321.9,283
XS GIS Cut Line= 3
2252485.88579785405249.5829509332252501.56580896405070.569490771
2252551.21917747404912.462712088
#Sta/Elev= 30
       0 2568.18    20.5  2564.2    36.5 2559.71    48.6 2555.08    64.7 2546.48
    88.7 2531.67    92.8 2528.48   104.8 2517.33   112.8 2510.71   116.8 2507.98
   120.9 2506.81   124.9 2506.28     145 2506.56   156.4 2507.61     174  2508.6
   188.4 2508.91   214.5 2508.01   235.7 2506.37   243.5 2506.21   269.2 2507.21
   277.6 2506.85   281.9 2507.46     286  2509.1   290.2  2511.7   297.8 2517.16
   304.1 2522.38   310.5 2526.71   323.7 2532.82   335.3 2539.14   345.4  2545.2
#Mann= 4 ,-1,0
       0      .1       0   120.9    .045       0   156.4      .1       0
   209.7     .12       0
Bank Sta=120.9,156.4
XS Rating Curve= 0 ,0
Exp/Cntr(USF)=0,0
Exp/Cntr=0.3,0.1

Type RM Length L Ch R = 1 ,32262   ,313.5,315.3,316.4
XS GIS Cut Line= 2
2252775.96600337405284.862975929 2252804.7126904405001.316108373
#Sta/Elev= 30
       0 2533.16     3.7 2530.85    11.7 2526.85    23.8 2520.14    31.8 2516.48
    43.7 2510.45    51.9 2507.29      56 2506.54      68 2505.46    80.1 2505.09
   104.2 2505.29   112.3 2505.78   127.7 2504.38   140.4 2502.61   144.4 2502.41
   160.7 2503.59   182.4 2502.79   196.3 2502.98   205.2 2502.06   216.8  2501.6
   220.8 2501.61   223.1 2502.02   224.8 2502.32   228.9 2504.54   232.9 2507.35
     249  2521.5     261 2529.03   272.3 2536.74   277.3 2539.66285.0003 2543.62
#Mann= 4 ,-1,0
       0      .1       0   205.2    .045       0   223.1      .1       0
     260     .12       0
#XS Ineff= 2 , 0
          111.63 2511.03
Permanent Ineff=
       F       F
Bank Sta=205.2,223.1
XS Rating Curve= 0 ,0
Exp/Cntr(USF)=0,0
Exp/Cntr=0.3,0.1

Type RM Length L Ch R = 1 ,31947   ,355.8,370.4,375.2
XS GIS Cut Line= 2
2253071.27287926405313.6096629622253118.31291258405074.489493548
#Sta/Elev= 30
       0 2543.02     8.6 2537.86    12.7 2535.78    16.7 2533.32    20.8  2530.4
    24.9 2527.78    41.2 2518.03    61.6 2507.45    65.7 2505.66    69.7 2504.29
    73.8 2503.21    77.9 2502.42   110.5 2498.52   114.6 2498.38   155.4 2500.67
   159.4  2500.7   163.5 2499.51   168.1 2497.78   171.5 2497.31   175.7 2497.09
   185.1 2497.01     192 2497.06   196.1 2497.65   200.2 2499.81   204.3 2503.04
   212.3 2510.08   216.5 2513.56   228.7  2523.1   236.9 2527.51243.7031 2531.55
#Mann= 4 ,-1,0
       0      .1       0      90     .12       0   168.1    .045       0
   196.1      .1       0
#XS Ineff= 2 , 0
          102.16  2511.8
Permanent Ineff=
       F       F
Bank Sta=168.1,196.1
XS Rating Curve= 0 ,0
Exp/Cntr(USF)=0,0
Exp/Cntr=0.3,0.1

Type RM Length L Ch R = 1 ,31577   ,242.6,248.7,251.2
XS GIS Cut Line= 2
2253386.17976903405389.3963833232253484.17983846405192.089576866
#Sta/Elev= 30
       0 2530.27    13.6 2523.14    40.4 2507.37    49.4 2503.07    53.8 2500.74
    58.3 2498.82    62.8 2497.35    67.2 2496.82    71.7 2496.77    94.4 2495.17
     118 2493.91   134.2 2494.11   139.4 2493.63   147.6 2492.25   153.8  2491.9
   159.8 2492.05   164.7 2492.64   165.8 2492.82  167.51 2493.84     170 2495.39
   175.3  2501.2   178.9  2504.5   183.4 2508.23   187.8 2512.84   189.6 2515.22
   192.3 2518.39   196.8 2523.32   201.2 2527.22   205.7 2530.83220.3043 2541.51
#Mann= 4 ,-1,0
       0      .1       0   139.4    .045       0  167.51      .1       0
     180     .12       0
#XS Ineff= 2 , 0
           93.85    2502
Permanent Ineff=
       F       F
Bank Sta=139.4,167.51
XS Rating Curve= 0 ,0
Exp/Cntr(USF)=0,0
Exp/Cntr=0.3,0.1

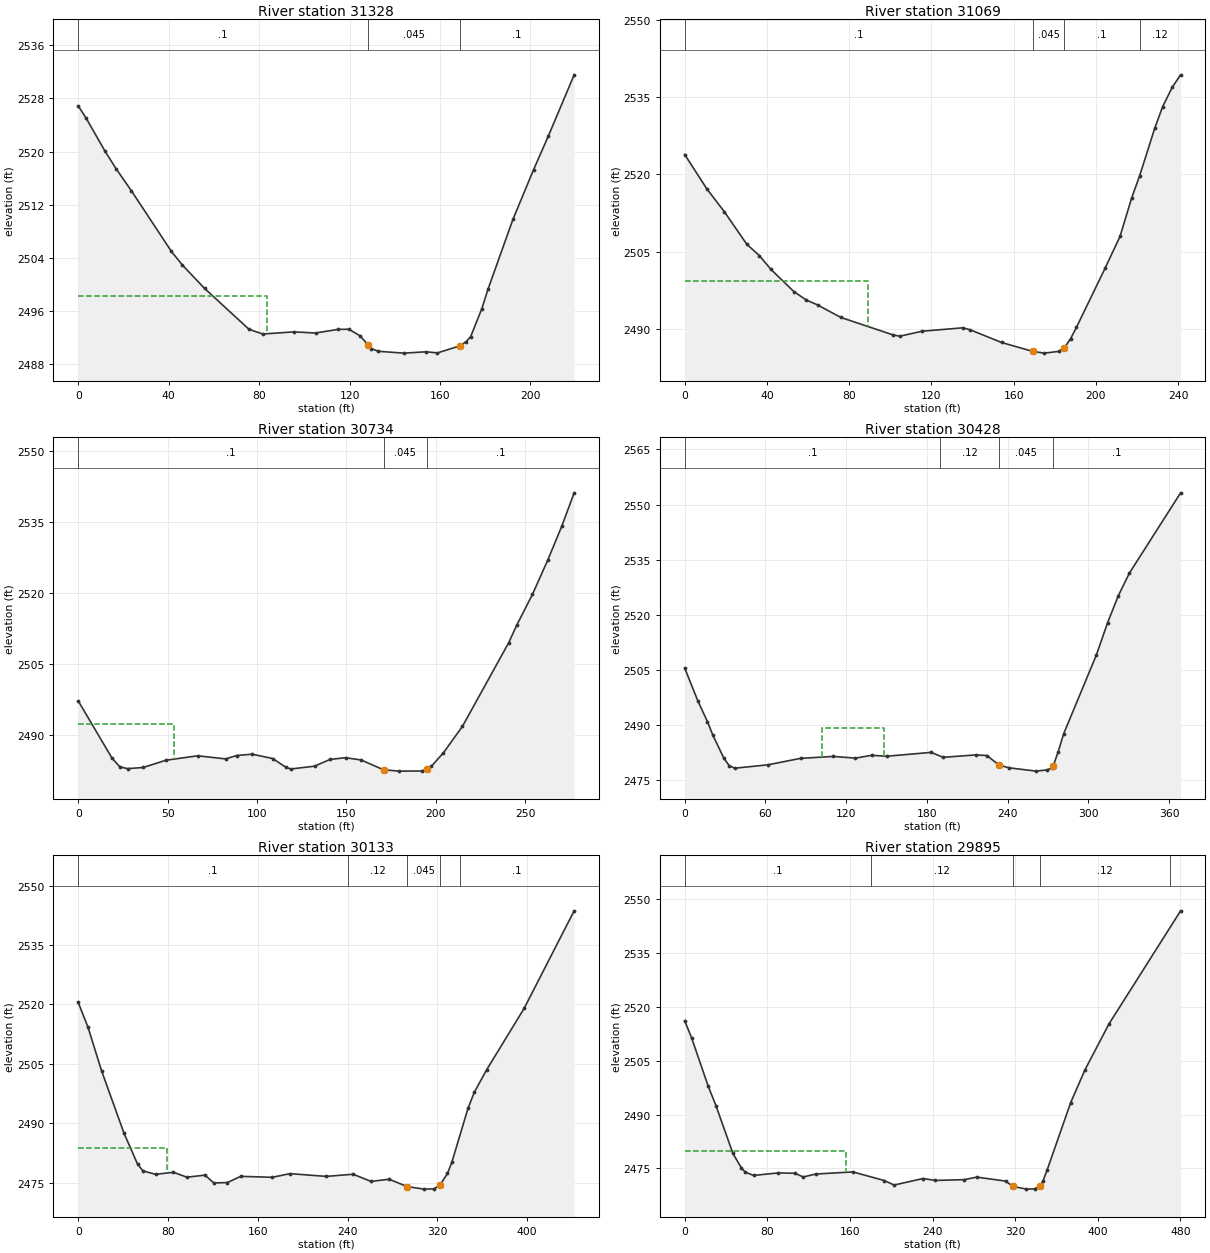
Type RM Length L Ch R = 1 ,31328   ,251.4,259.2,261.7
XS GIS Cut Line= 2
2253573.03323475405514.8364721952253699.77999121405335.823012033
#Sta/Elev= 30
       0 2526.88     3.4 2525.09    11.8  2520.1    16.7 2517.44    23.5 2514.11
    41.2 2504.97    46.1  2502.9    55.9 2499.39    75.5 2493.25    81.6 2492.53
    95.4 2492.85     105 2492.68   114.8 2493.22   119.7 2493.25   124.6 2492.27
   128.1 2490.94   129.7 2490.34   132.6 2489.93   143.9 2489.65     154 2489.85
   158.9 2489.68   168.7 2490.74   171.6 2491.38   173.6 2492.15   178.5 2496.34
   181.3 2499.33   192.3 2509.82   201.4 2517.28   207.9 2522.32219.3412 2531.56
#Mann= 3 ,0,0
       0      .1       0   128.1    .045       0   168.7      .1       0
#XS Ineff= 2 , 0
           83.47 2498.29
Permanent Ineff=
       F       F
Bank Sta=128.1,168.7
XS Rating Curve= 0 ,0
Exp/Cntr(USF)=0,0
Exp/Cntr=0.3,0.1

Type RM Length L Ch R = 1 ,31069   ,312.6,334.9,341.2
BEGIN DESCRIPTION:
IFA placed to resolve crossing profile
END DESCRIPTION:
XS GIS Cut Line= 2
2253735.06001621405683.3965916182253903.62013563405510.916469418
#Sta/Elev= 30
       0 2523.87    10.8 2517.18    19.3 2512.75    30.2 2506.44    36.3 2504.23
      42 2501.53    53.1 2497.24      59 2495.63    64.6 2494.65    75.9 2492.22
   101.4 2488.81   104.6 2488.57   115.5 2489.54   135.3  2490.2   138.9  2489.8
   154.1 2487.35   169.2 2485.62   174.9 2485.28   182.1 2485.63   184.7 2486.33
   187.7 2488.12   190.5 2490.28   204.4 2501.74   211.7 2507.96   217.3 2515.35
   221.2 2519.69   228.6 2528.99   232.4 2533.14   237.1 2536.95241.1678 2539.35
#Mann= 4 ,-1,0
       0      .1       0   169.2    .045       0   184.7      .1       0
   221.2     .12       0
#XS Ineff= 2 , 0
           89.29 2499.32
Permanent Ineff=
       F       F
Bank Sta=169.2,184.7
XS Rating Curve= 0 ,0
Exp/Cntr(USF)=0,0
Exp/Cntr=0.3,0.1

Type RM Length L Ch R = 1 ,30734   ,300.2,305.6,309
XS GIS Cut Line= 2
2253878.79345138405904.223414738 2254133.5936319405794.463336974
#Sta/Elev= 30
       0 2497.14    18.9 2485.01    23.3 2483.15    27.6 2482.78    36.3 2483.02
      49 2484.55    66.8  2485.5    82.5 2484.84    88.6 2485.56    97.3 2485.84
   108.8 2484.92     116 2483.11   118.9  2482.7   132.2  2483.3   140.9 2484.73
   149.6  2485.1   158.3 2484.61   170.8 2482.53   179.6 2482.25   192.1 2482.28
   195.1 2482.68   197.5 2483.25   204.3 2486.13   214.9 2491.71   240.8 2509.45
   245.4 2513.24   254.1  2519.7   262.8 2527.09   270.6 2534.24277.4354 2541.23
#Mann= 3 ,-1,0
       0      .1       0   170.8    .045       0   195.1      .1       0
#XS Ineff= 2 , 0
           53.82 2492.29
Permanent Ineff=
       F       F
Bank Sta=170.8,195.1
XS Rating Curve= 0 ,0
Exp/Cntr(USF)=0,0
Exp/Cntr=0.3,0.1

Type RM Length L Ch R = 1 ,30428   ,288.5,295.4,299.5
XS GIS Cut Line= 2
2253903.62013563 406164.250265632254265.56705873406094.996883232
#Sta/Elev= 30
       0 2505.47     9.9 2496.39    16.9 2490.87    20.9 2487.18    29.1  2480.9
    33.1 2478.83    37.2 2478.16    61.7 2479.07    86.1 2480.84   110.5 2481.37
   126.8  2480.9     139 2481.67   150.1 2481.42   183.2 2482.47     192 2481.12
   216.4 2481.78   224.6 2481.61   233.5 2479.03   240.8 2478.27   261.2 2477.36
   269.4  2477.7   273.2 2478.27   273.8 2478.76   277.5 2482.58   281.6 2487.53
     306 2509.08   314.3 2517.85   322.3  2525.2   330.4 2531.29368.5127 2553.19
#Mann= 4 ,-1,0
       0      .1       0     190     .12       0   233.5    .045       0
   273.8      .1       0
#XS Ineff= 1 ,-1
  102.33  148.17 2489.07
Permanent Ineff=
       F
Bank Sta=233.5,273.8
XS Rating Curve= 0 ,0
Exp/Cntr(USF)=0,0
Exp/Cntr=0.3,0.1

Type RM Length L Ch R = 1 ,30133   ,241.3,237.5,237.3
XS GIS Cut Line= 2
2253851.35343193406398.1437646742254293.00707817406415.130443376
#Sta/Elev= 30
       0 2520.53     8.8 2514.19    20.8 2503.25    40.9 2487.41    52.9 2479.66
    57.7 2477.96    68.9 2477.08    84.9  2477.6    96.9 2476.35   112.9 2476.88
   120.9  2474.9   132.9    2475   144.9 2476.57   172.9 2476.33   188.7 2477.25
     221 2476.56     245  2477.1     261 2475.29     277 2475.84   293.3 2473.97
   308.2 2473.34   317.1  2473.4   322.4 2474.39   329.1 2477.29   333.1 2480.23
   347.4 2493.77   353.1 2497.88     364 2503.51   397.4 2519.01441.9802 2543.67
#Mann= 5 ,-1,0
       0      .1       0     240     .12       0   293.3    .045       0
   322.4     .12       0     340      .1       0
#XS Ineff= 2 , 0
            78.9 2483.66
Permanent Ineff=
       F       F
Bank Sta=293.3,322.4
XS Rating Curve= 0 ,0
Exp/Cntr(USF)=0,0
Exp/Cntr=0.3,0.1

Type RM Length L Ch R = 1 ,29895   ,90.1,91.7,93.2
XS GIS Cut Line= 2
 2253813.4568084406636.7201073452254293.39296877406651.374646593
#Sta/Elev= 30
       0 2516.12     6.7 2511.35    22.7 2497.95    30.3 2492.47    46.7 2479.17
    54.7 2475.26    58.7 2473.95    66.7 2473.06    90.8 2473.77   106.8 2473.65
   114.8 2472.63   126.8 2473.45   162.8 2474.04   193.4 2471.63   202.8 2470.39
   230.8  2472.2   242.8 2471.67   270.8 2471.89   282.8 2472.59   310.9 2471.48
   317.6 2470.03   330.9 2469.25   338.9 2469.33  343.97 2470.08   346.9 2471.48
   350.9 2474.53   373.8 2493.35   387.5 2502.39   410.8  2515.2   480.2 2546.68
#Mann= 5 ,-1,0
       0      .1       0     180     .12       0   317.6    .045       0
  343.97     .12       0     470      .1       0
#XS Ineff= 2 , 0
          156.62 2479.85
Permanent Ineff=
       F       F
Bank Sta=317.6,343.97
XS Rating Curve= 0 ,0
Exp/Cntr(USF)=0,0
Exp/Cntr=0.3,0.1