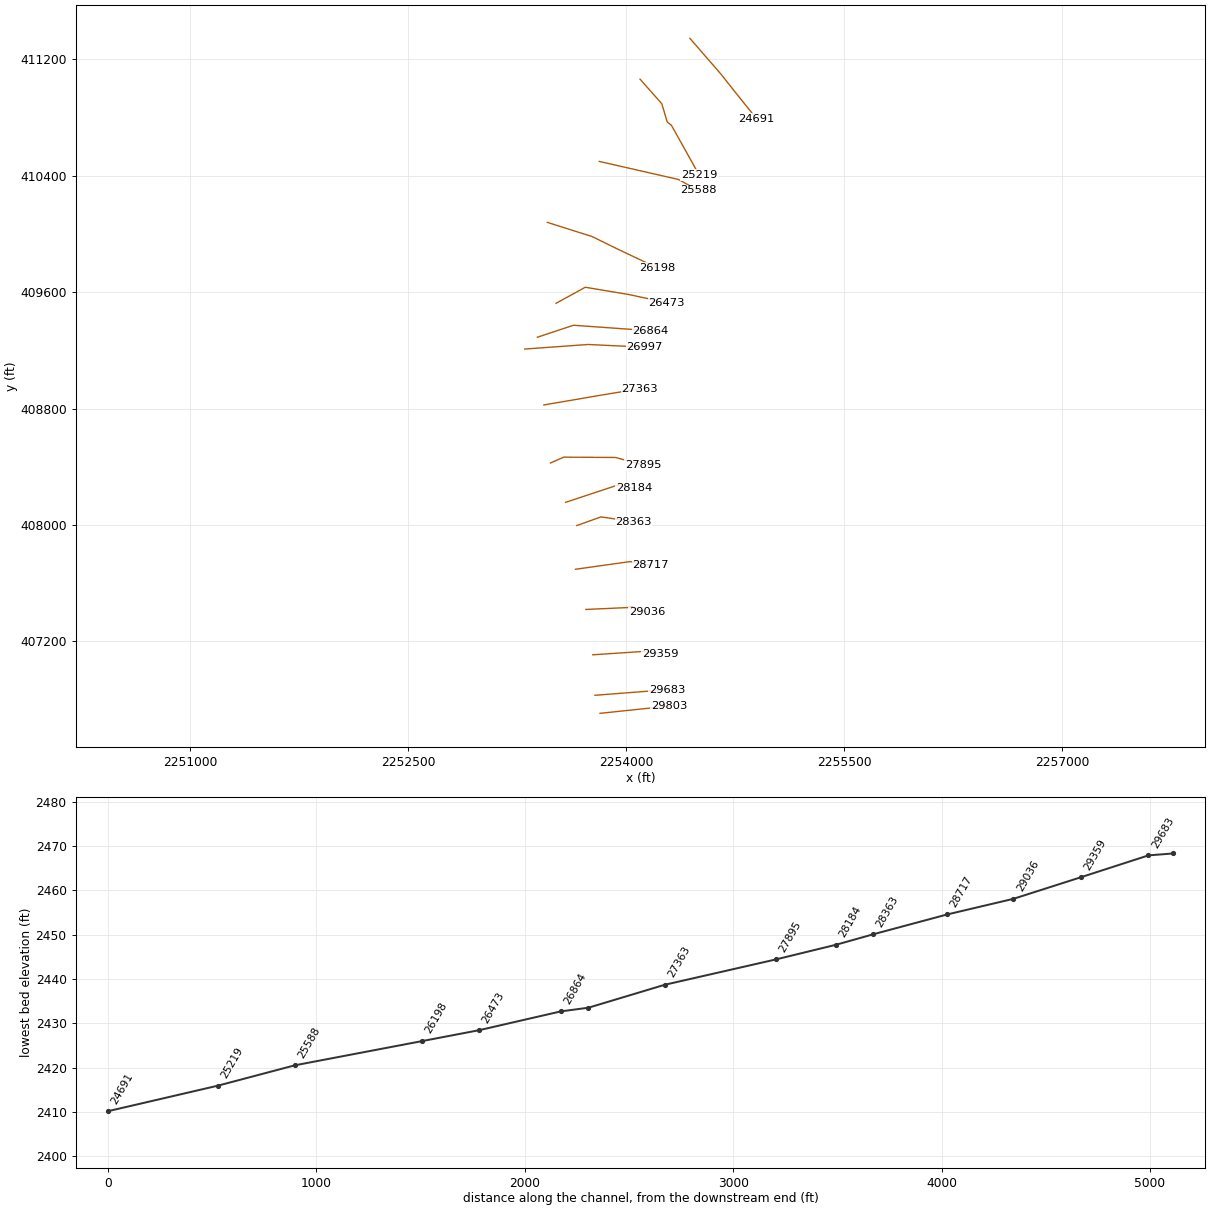
HEC-RAS study DOUTHTCK.prj: DOUTHTCK

--- DOUTHTCK.g01 (geometry) --- (continued)

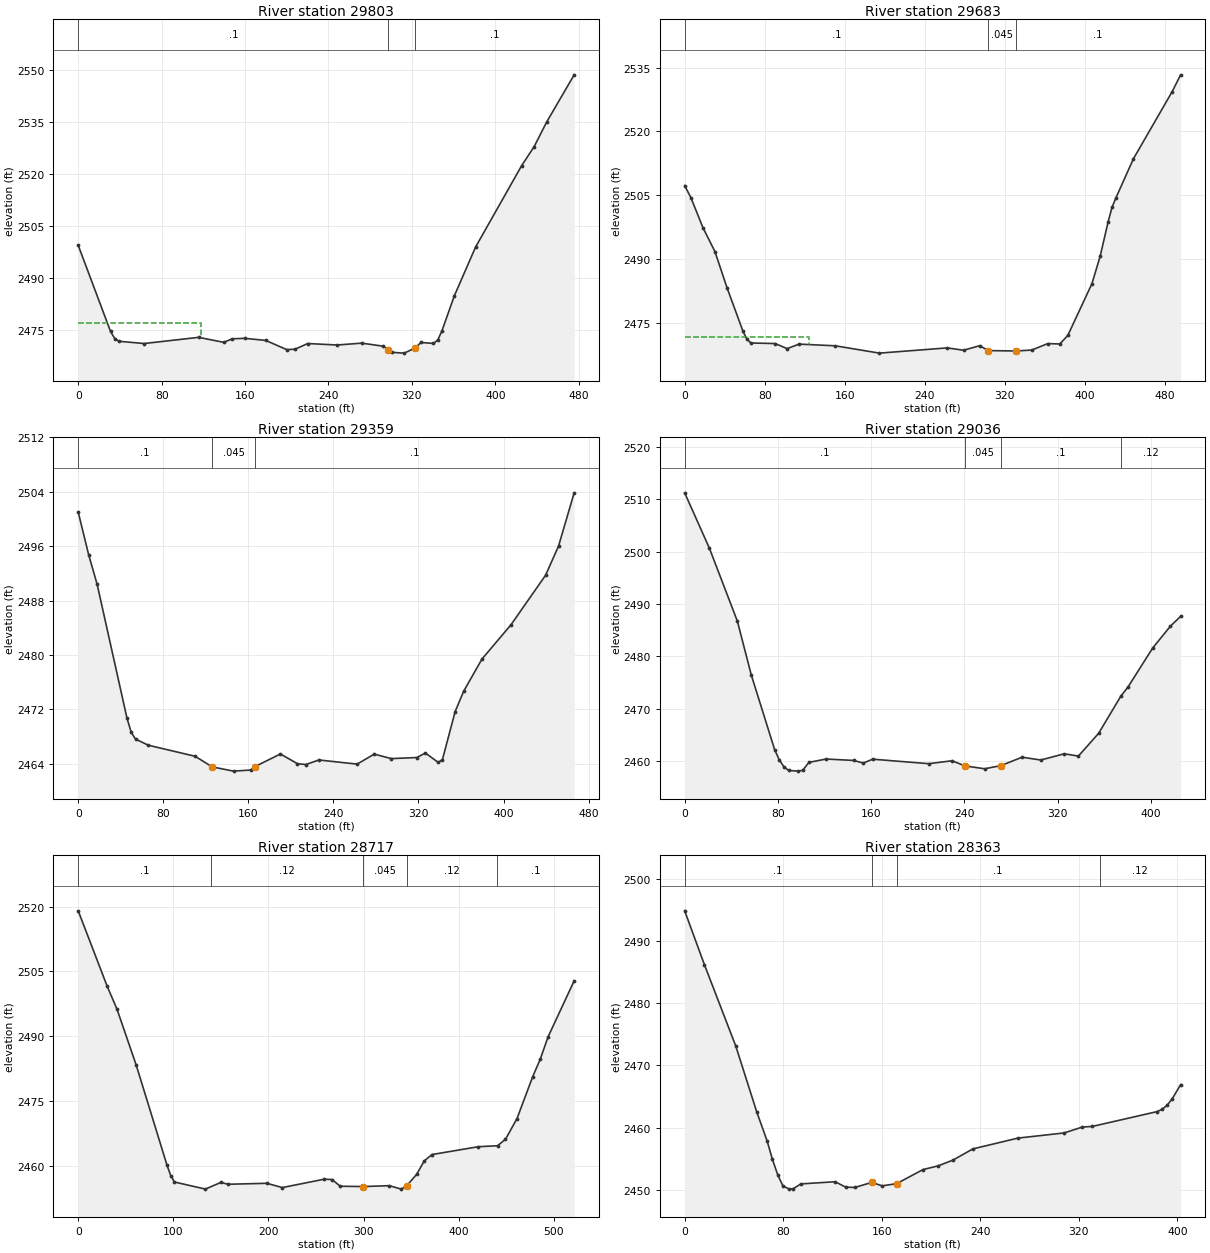
Type RM Length L Ch R = 1 ,29803   ,132.3,119.9,117.3
XS GIS Cut Line= 2
2253821.30007731406705.2106488942254294.31374577406754.864017406
#Sta/Elev= 30
       0  2499.4      31 2474.58    35.1 2472.49    39.1 2471.74    63.2 2471.09
   115.5 2472.87   139.6 2471.43   147.7 2472.45   159.7 2472.59   179.9 2471.98
     200 2469.33     208 2469.46   220.1 2471.09   248.2 2470.66   271.9  2471.2
   292.5 2470.32   297.4 2469.36   300.5 2468.55   312.6 2468.32   322.9 2469.76
   328.7 2471.39   340.7 2471.12   344.8 2472.09   348.8 2474.73   360.8 2484.91
   381.1 2498.92   425.2 2522.36   437.3 2527.91   449.3 2534.99475.6126 2548.58
#Mann= 3 ,-1,0
       0      .1       0   297.4    .045       0   322.9      .1       0
#XS Ineff= 2 , 0
          117.75 2476.96
Permanent Ineff=
       F       F
Bank Sta=297.4,322.9
XS Rating Curve= 0 ,0
Exp/Cntr(USF)=0,0
Exp/Cntr=0.3,0.1

Type RM Length L Ch R = 1 ,29683   ,295.3,324.7,301
XS GIS Cut Line= 2
2253785.97954731406829.0609349762254280.57024693406867.529100502
#Sta/Elev= 30
       0 2507.26     6.2 2504.43    18.3 2497.35    30.3 2491.73    42.3 2483.28
    58.4 2472.98    62.4  2471.1    66.4 2470.26    90.5 2470.13   102.5 2468.94
   114.5    2470   150.6  2469.6   194.8 2467.88   262.7 2469.11     279 2468.56
   295.1 2469.62   303.7 2468.48   331.2 2468.38   347.2  2468.6   363.2 2470.12
   375.3 2470.03   383.3 2472.06   407.4 2484.21   415.6 2490.62   423.5 2498.65
   427.5 2502.17   431.5 2504.43   448.9 2513.56   487.7 2529.35   496.1 2533.28
#Mann= 3 ,-1,0
       0      .1       0   303.7    .045       0   331.2      .1       0
#XS Ineff= 2 , 0
          124.76 2471.65
Permanent Ineff=
       F       F
Bank Sta=303.7,331.2
XS Rating Curve= 0 ,0
Exp/Cntr(USF)=0,0
Exp/Cntr=0.3,0.1

Type RM Length L Ch R = 1 ,29359   ,315.8,323.3,310
XS GIS Cut Line= 3
2253770.40909935407107.4971806892254129.44531093407131.310806967
2254234.77481178407114.824450313
#Sta/Elev= 30
       0 2501.01     9.8 2494.75    17.8 2490.39    45.9  2470.7    49.9 2468.62
    53.9 2467.65    65.9 2466.75     110 2465.12     126 2463.56   146.1 2462.94
   162.1  2463.1   166.1  2463.6   190.2 2465.46   206.2 2464.03   214.2 2463.91
   226.3 2464.58   262.3 2463.97   278.4 2465.44   294.4 2464.78   318.5 2464.94
   326.5  2465.6   338.5 2464.23   342.5 2464.62   354.5  2471.7   362.6 2474.71
   379.7 2479.41   407.1 2484.47   439.5 2491.72   451.7    2496   466.4 2503.84
#Mann= 3 ,-1,0
       0      .1       0     126    .045       0   166.1      .1       0
Bank Sta=126,166.1
XS Rating Curve= 0 ,0
Exp/Cntr(USF)=0,0
Exp/Cntr=0.3,0.1

Type RM Length L Ch R = 1 ,29036   ,308.2,318.3,312.9
XS GIS Cut Line= 3
2253723.00639826 407419.091568782254045.18171026407433.560678958
2254142.87469597407400.882957878
#Sta/Elev= 30
       0 2511.22    21.2 2500.65    45.2 2486.72    57.2  2476.4    77.2 2462.17
    81.3 2460.17    85.3 2458.85    89.3 2458.21    97.3 2458.08   101.3 2458.25
   106.6 2459.75   121.3 2460.39   144.9 2460.12   153.3 2459.62   161.3 2460.36
   209.4  2459.5   229.4 2460.06   240.52459.076   257.4 2458.53   271.4 2459.14
   289.5 2460.74   305.5  2460.2   325.7 2461.39   337.8 2460.95   355.2 2465.31
   374.1 2472.35   380.5 2474.19   401.6 2481.61   416.8 2485.77   425.5 2487.63
#Mann= 4 ,-1,0
       0      .1       0   240.5    .045       0   271.4      .1       0
   374.1     .12       0
Bank Sta=240.5,271.4
XS Rating Curve= 0 ,0
Exp/Cntr(USF)=0,0
Exp/Cntr=0.3,0.1

Type RM Length L Ch R = 1 ,28717   ,323.5,354.5,350.8
XS GIS Cut Line= 3
2253651.77439365407695.2366834142254028.53507469407748.200169497
2254167.05425337407721.785621918
#Sta/Elev= 30
       0 2519.02    30.4 2501.57    40.8 2496.23      61 2483.27    93.3 2460.14
    97.3 2457.69   101.2  2456.2   133.7 2454.56   149.9 2456.09   157.9 2455.68
   198.3  2455.9   214.6 2454.91   258.9 2456.86     267 2456.76   275.5 2455.22
   299.42455.146   327.2 2455.35   339.7 2454.55   345.6 2455.36   355.9 2457.98
   363.9  2461.1     372 2462.56   420.8 2464.38   440.9  2464.6   449.3  2466.1
   461.4 2470.89   477.8 2480.54     486 2484.74   494.1 2489.84   521.5  2502.8
#Mann= 5 ,-1,0
       0      .1       0     140     .12       0   299.4    .045       0
   345.6     .12       0  440.47      .1       0
Bank Sta=299.4,345.6
XS Rating Curve= 0 ,0
Exp/Cntr(USF)=0,0
Exp/Cntr=0.3,0.1

Type RM Length L Ch R = 1 ,28363   ,174.2,179,182.5
XS GIS Cut Line= 3
 2253661.1040244 407995.778981442253827.82637868408055.214865877
2254051.04994299408021.891290499
#Sta/Elev= 30
       0 2494.91      16 2486.25    41.5 2473.12    58.5 2462.53      67 2457.81
    71.2  2454.9    75.5 2452.42    79.7 2450.61    84.9 2450.08    88.2 2450.15
    94.3 2450.92   122.2 2451.27   130.7  2450.4   138.1 2450.35   151.9 2451.16
   160.4 2450.61   172.12450.963   193.5 2453.23   205.7 2453.82   217.8 2454.75
     234 2456.56   270.6  2458.3   308.1 2459.13   322.9 2460.08     331 2460.18
   383.2 2462.55   387.7 2462.93   391.7  2463.6   395.7 2464.57   402.7 2466.91
#Mann= 4 ,-1,0
       0      .1       0   151.9    .045       0   172.1      .1       0
     337     .12       0
Bank Sta=151.9,172.1
XS Rating Curve= 0 ,0
Exp/Cntr(USF)=0,0
Exp/Cntr=0.3,0.1

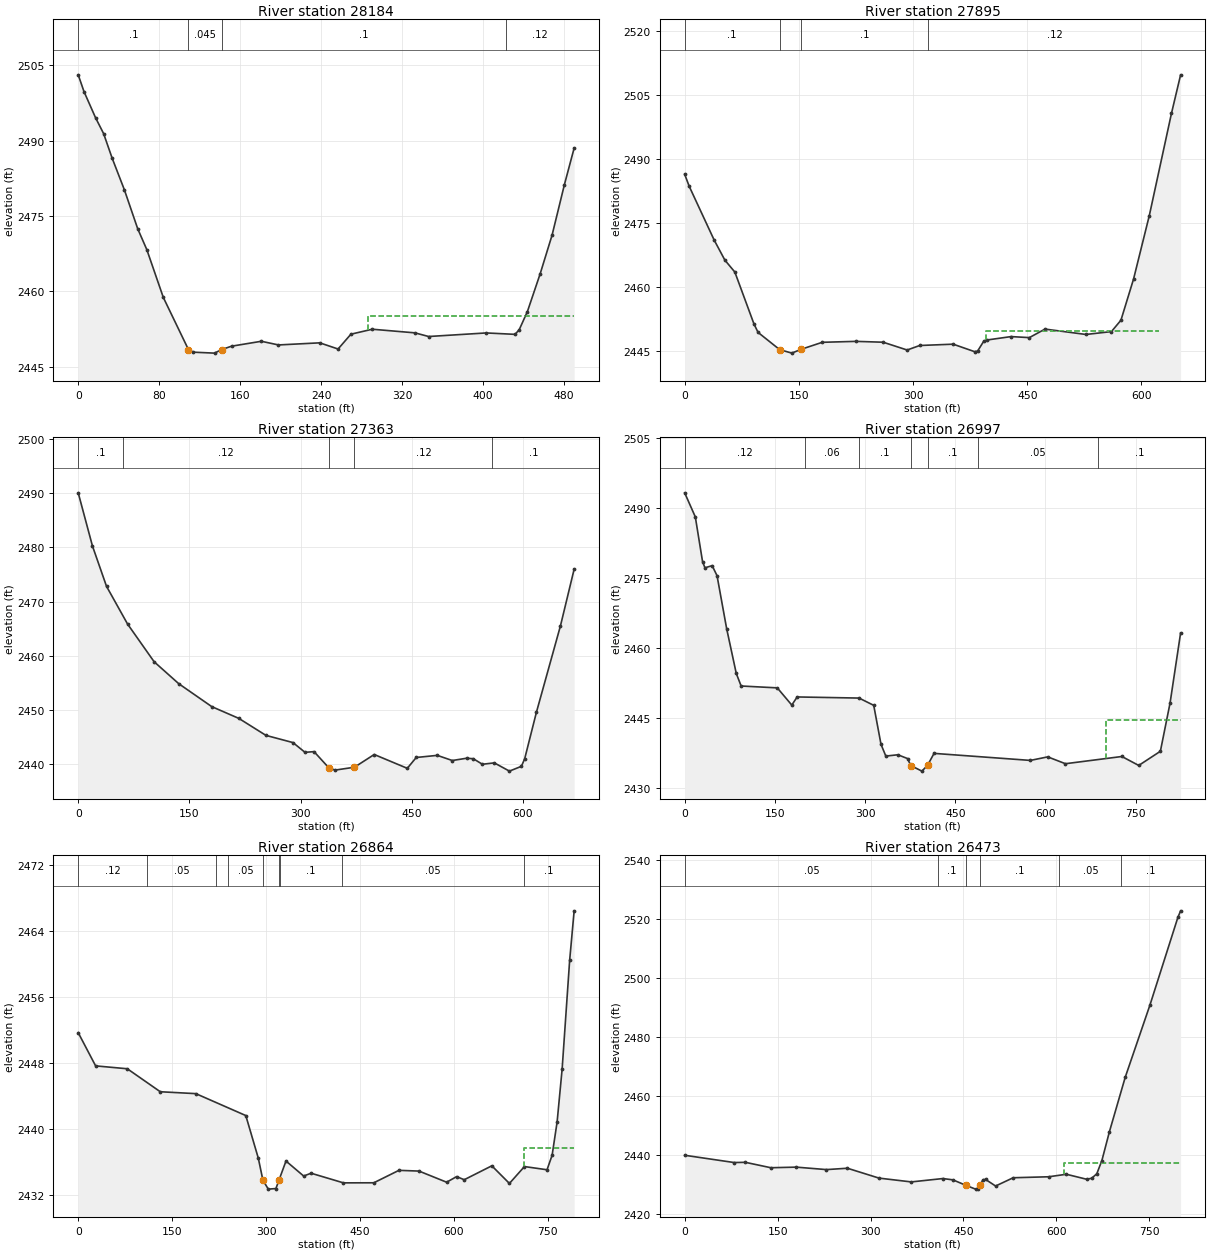
Type RM Length L Ch R = 1 ,28184   ,293.2,289,232.4
XS GIS Cut Line= 3
 2253584.3405977408155.3777032542253938.28701303408272.558604762
2254053.66513144408251.526135261
#Sta/Elev= 30
       0 2503.14     5.7 2499.81    17.1 2494.61    25.1 2491.43    33.5 2486.56
    45.6 2480.25    58.8 2472.48    67.8 2468.32    84.1  2458.8   108.9 2448.43
   113.6  2447.9   134.7 2447.71   141.8 2448.42   151.5 2449.09     181 2450.07
   197.9 2449.34   238.7 2449.76   256.8 2448.53   269.5 2451.48   290.6 2452.47
   332.7 2451.75   346.3 2451.02   403.2 2451.73   431.7 2451.45   435.8 2452.37
   443.9 2455.99   456.5  2463.5   468.3 2471.22   480.5 2481.29   490.1 2488.55
#Mann= 4 ,-1,0
       0      .1       0   108.9    .045       0   141.8      .1       0
  422.84     .12       0
#XS Ineff= 2 , 0
                          285.92         2455.04
Permanent Ineff=
       F       F
Bank Sta=108.9,141.8
XS Rating Curve= 0 ,0
Exp/Cntr(USF)=0,0
Exp/Cntr=0.3,0.1

Type RM Length L Ch R = 1 ,27895   ,495.4,531.6,459.4
XS GIS Cut Line= 4
2253479.80019894408425.6966555892253571.62847309 408465.76942178
2253928.58518435408463.6117734422254115.79561927408411.668039631
#Sta/Elev= 30
       0 2486.36       6 2483.52    38.7 2470.94    52.8 2466.22    65.9 2463.42
      91 2451.25    96.4 2449.26   124.7 2445.23   140.7  2444.4   152.7 2445.28
   180.7 2446.94   224.9 2447.16   260.7 2446.96   292.2 2445.13   308.7 2446.19
   352.7  2446.5   380.7 2444.75   384.7 2444.87   392.7 2447.16   396.7 2447.47
   428.7 2448.28   452.7 2448.04   473.3 2450.04     527 2448.78   560.5 2449.45
     573 2452.12   589.6 2461.79   610.3 2476.69   639.4 2500.67   651.4  2509.7
#Mann= 4 ,-1,0
       0      .1       0   124.7    .045       0   152.7      .1       0
  320.19     .12       0
#XS Ineff= 1 ,-1
  395.66623.52722449.621
Permanent Ineff=
       F
Bank Sta=124.7,152.7
XS Rating Curve= 0 ,0
Exp/Cntr(USF)=0,0
Exp/Cntr=0.3,0.1

Type RM Length L Ch R = 1 ,27363   ,367,366.2,321.7
XS GIS Cut Line= 3
2253434.52646995408824.6254838072253847.43342916408895.185533798
2254094.39360412408935.692229163
#Sta/Elev= 30
       0 2490.09    19.2 2480.28    38.2 2472.82    66.6 2465.86   102.4  2458.9
   135.6 2454.85   180.2 2450.61   216.7 2448.44   253.3  2445.3   289.8 2443.97
     306 2442.17   318.2  2442.3   338.1 2439.32   346.6 2438.89   372.7 2439.42
   399.4 2441.77     444 2439.22   456.1 2441.22   484.5 2441.61   504.7 2440.66
     524 2441.08   533.1 2440.99   545.3 2439.97   561.5 2440.22   581.8  2438.7
     598 2439.59   602.4 2440.98   618.3  2449.6   650.7 2465.54669.1525    2476
#Mann= 5 ,-1,0
       0      .1       0      60     .12       0   338.1    .045       0
   372.7     .12       0  558.89      .1       0
Bank Sta=338.1,372.7
XS Rating Curve= 0 ,0
Exp/Cntr(USF)=0,0
Exp/Cntr=0.3,0.1

Type RM Length L Ch R = 1 ,26997   ,136.3,133.2,120.3
XS GIS Cut Line= 3
2253302.55304312 409208.785755982253738.98001899409240.145778198
2254125.75362634409221.852431904
#Sta/Elev= 30
       0 2493.26    17.7 2488.09    29.7 2478.51    33.7 2477.17    45.7 2477.63
    53.8 2475.48    69.8 2464.11    85.8 2454.49    93.9  2451.8     154  2451.4
   178.1 2447.71   187.1 2449.45     290 2449.21   314.4 2447.65   326.5 2439.28
   334.5 2436.76   354.5 2437.04   370.6 2436.23     376 2434.73   394.5 2433.53
  403.97 2434.79   414.7 2437.34   574.9 2435.83   603.8 2436.59   633.2 2435.12
   727.1 2436.67   755.1 2434.75   791.1 2437.79   807.2 2448.14824.7582  2463.2
#Mann= 7 ,-1,0
       0     .12       0     200     .06       0     290      .1       0
     376    .045       0  403.97      .1       0  487.55     .05       0
  687.55      .1       0
#XS Ineff= 1 ,-1
     701     7012444.507
Permanent Ineff=
       F
Bank Sta=376,403.97
XS Rating Curve= 0 ,0
Exp/Cntr(USF)=0,0
Exp/Cntr=0.3,0.1

Type RM Length L Ch R = 1 ,26864   ,383.3,390.9,241.1
XS GIS Cut Line= 3
2253389.78858578409289.9659238722253638.27471462409372.329303657
2254167.35473053409334.637587485
#Sta/Elev= 30
       0 2451.68    27.8 2447.65    78.4  2447.3   131.1 2444.51   187.9 2444.28
   267.7 2441.62   287.7 2436.44     295 2433.78   303.6 2432.69   315.8 2432.76
  320.87 2433.82   331.9  2436.1   360.1 2434.28     372 2434.62   423.7 2433.45
   472.2 2433.46   512.3 2434.97   544.4 2434.88   588.5 2433.53   604.5 2434.21
   616.6 2433.83   660.7 2435.52   688.8 2433.38   712.8 2435.43   748.9 2435.04
     757  2436.8     765 2440.85     773 2447.26     785 2460.45   792.2 2466.47
#Mann= 9 ,-1,0
       0     .12       0     110     .05       0     220     .06       0
     240     .05       0     295    .045       0  320.87     .05       0
  321.78      .1       0  421.78     .05       0  711.78      .1       0
#XS Ineff= 2 , 0
                          711.66         2437.74
Permanent Ineff=
       F       F
Bank Sta=295,320.87
XS Rating Curve= 0 ,0
Exp/Cntr(USF)=0,0
Exp/Cntr=0.3,0.1

Type RM Length L Ch R = 1 ,26473   ,281.7,275,263.9
XS GIS Cut Line= 4
2253518.21961867409523.0961683492253719.24210492409633.379337893
2254020.77583431409583.1237163292254280.42987905409527.284136813
#Sta/Elev= 30
       0 2439.92    79.8 2437.46      98 2437.53   139.1  2435.7   180.2  2435.9
   228.9 2435.07   262.7 2435.53   313.7 2432.19   365.8  2430.9   416.8 2432.04
     433  2431.6   454.22429.729   469.5 2428.46   473.6 2428.64  476.32 2429.77
   481.7 2431.63   485.7 2431.75   501.9 2429.51   530.3 2432.31   587.6 2432.64
   616.2 2433.49   648.9  2431.8   657.1 2432.15   665.3 2433.66   673.5 2438.13
   685.7 2447.92   711.2 2466.33   751.2 2490.83   796.2 2520.43   800.6 2522.64
#Mann= 6 ,-1,0
       0     .05       0  409.29      .1       0   454.2    .045       0
  476.32      .1       0  604.98     .05       0  704.98      .1       0
#XS Ineff= 2 , 0
                          611.83         2437.34
Permanent Ineff=
       F       F
Bank Sta=454.2,476.32
XS Rating Curve= 0 ,0
Exp/Cntr(USF)=0,0
Exp/Cntr=0.3,0.1

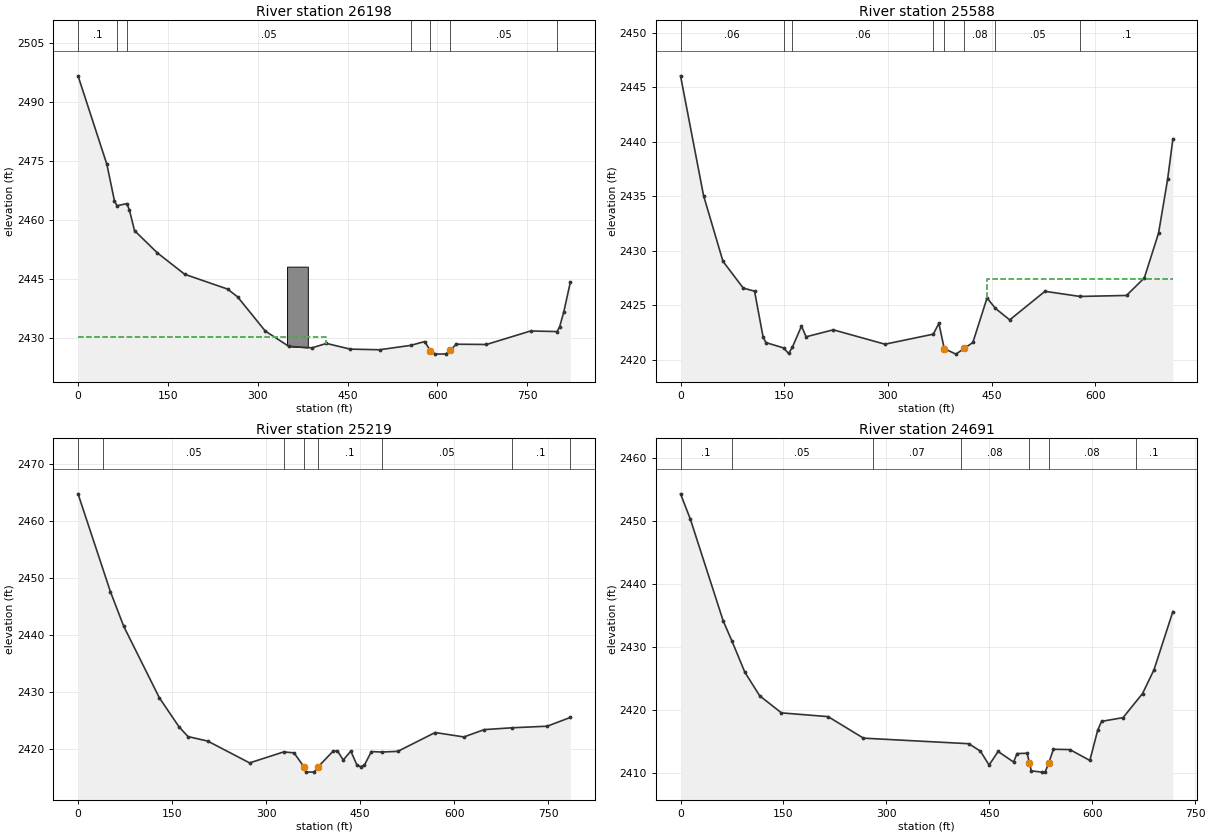
Type RM Length L Ch R = 1 ,26198   ,597.4,610.1,609.6
BEGIN DESCRIPTION:
start of detailed zone
END DESCRIPTION:
XS GIS Cut Line= 6
2253458.24058126410079.4354352252253763.04442624 409982.92486414
2253773.34320483409978.5970212022253943.85896765409894.820022127
2254089.50308945409825.9162543832254216.32702412409766.322836134
#Sta/Elev= 30
       0 2496.67    48.2 2474.16    60.7    2465      65 2463.68    81.7 2464.22
    85.9 2462.53    94.3 2457.37   132.1 2451.75   178.2 2446.26   249.6 2442.52
   266.4 2440.54   312.6 2431.86     352 2427.96   390.8 2427.59   414.8 2428.71
   454.4 2427.26   503.4  2427.1   555.4 2428.21   578.7 2429.18   588.4 2426.88
   596.4 2425.99   614.1 2426.04   621.5 2427.03   631.8 2428.51     682 2428.44
   755.7 2431.87   799.9 2431.72   804.3 2432.99   811.1 2436.71   822.1 2444.31
#Mann= 7 ,-1,0
       0      .1       0      65    .016       0    81.7     .05       0
   555.4     .08       0   588.4    .045       0   621.5     .05       0
   799.9      .1       0
#XS Ineff= 2 , 0
          413.27 2430.28
Permanent Ineff=
       F       F
#Block Obstruct= 1 ,-1
  349.04  383.67 2448.21
Bank Sta=588.4,621.5
XS Rating Curve= 0 ,0
Exp/Cntr(USF)=0,0
Exp/Cntr=0.3,0.1

Type RM Length L Ch R = 1 ,25588   ,408.8,369,343.4
XS GIS Cut Line= 3
2253815.71593728410498.2477572332254361.51790354410373.977037835
2254494.80612262410299.635392375
#Sta/Elev= 30
       0 2446.05    33.3 2435.07    61.4 2429.04    90.7 2426.59   107.1  2426.3
   119.4 2422.12   123.5 2421.59     149  2421.1   156.4 2420.59   161.7 2421.15
     175  2423.1   181.7 2422.12     221 2422.76   295.8 2421.44   365.7 2422.36
   373.8 2423.35   381.6 2421.04   398.4 2420.53   410.52421.051     423  2421.6
   443.5 2425.68   455.7 2424.72   476.3 2423.67   527.3 2426.29   577.8 2425.82
   645.3 2425.91   671.1 2427.52   691.7 2431.63   704.8 2436.56   712.4 2440.27
#Mann= 8 ,-1,0
       0     .06       0     149    .045       0   161.7     .06       0
   365.7     .08       0   381.6    .045       0   410.5     .08       0
   455.7     .05       0   577.8      .1       0
#XS Ineff= 2 , 0
                          443.49         2427.39
Permanent Ineff=
       F       F
Bank Sta=381.6,410.5
XS Rating Curve= 0 ,0
Exp/Cntr(USF)=0,0
Exp/Cntr=0.3,0.1

Type RM Length L Ch R = 1 ,25219   ,498.6,527.7,514
XS GIS Cut Line= 5
2254095.80713718411063.8115441712254245.77922851410894.801075461
2254283.09683868410769.3273716922254311.76108998 410747.15313956
2254502.87058118410404.947152744
#Sta/Elev= 30
       0 2464.84    51.6 2447.66      73 2441.53   129.6 2429.02   160.8 2423.94
   175.3 2422.19   206.7  2421.4   273.6 2417.56   327.8 2419.49   344.5 2419.33
   360.32416.849   363.6 2415.94   376.7 2415.97   383.3 2416.92   406.6 2419.61
   413.7 2419.67   422.9 2418.07     435 2419.63   444.8 2417.18   450.7  2416.9
   456.6 2417.16   467.8 2419.55   484.2 2419.47   509.9 2419.59   569.5  2422.9
   615.3 2422.12   647.7 2423.41   691.8 2423.73   748.1 2424.01   785.1 2425.55
#Mann= 8 ,-1,0
       0     .06       0      40     .05       0   327.8     .07       0
   360.3    .045       0   383.3      .1       0   484.2     .05       0
   691.8      .1       0   785.1      .1       0
Bank Sta=360.3,383.3
XS Rating Curve= 0 ,0
Exp/Cntr(USF)=0,0
Exp/Cntr=0.3,0.1

Type RM Length L Ch R = 1 ,24691   ,257.8,252.9,247.2
XS GIS Cut Line= 4
2254439.03902193411344.2205842382254654.34305218411096.578019301
2254756.63190938410967.0548714082254897.46431998410792.336442266
#Sta/Elev= 30
       0 2454.25    14.3 2450.24    62.3 2434.09    74.9 2430.95    93.7 2426.01
   115.3 2422.28   147.1 2419.56   215.1 2418.97   266.6 2415.56   420.2 2414.68
   437.2 2413.49   449.7  2411.3   462.9 2413.45   485.4 2411.78   490.5 2413.12
   505.2 2413.17   508.4 2411.66   511.3 2410.38   526.4 2410.18   531.6 2410.24
   536.7 2411.64   543.5  2413.8   567.5 2413.75   596.6 2412.03     608 2416.81
   613.7 2418.22     645 2418.81   673.4 2422.63   690.1 2426.39   717.6 2435.61
#Mann= 7 ,-1,0
       0      .1       0    74.9     .05       0     280     .07       0
  408.15     .08       0   508.4    .045       0   536.7     .08       0
  663.19      .1       0
Bank Sta=508.4,536.7
XS Rating Curve= 0 ,0
Exp/Cntr(USF)=0,0
Exp/Cntr=0.3,0.1