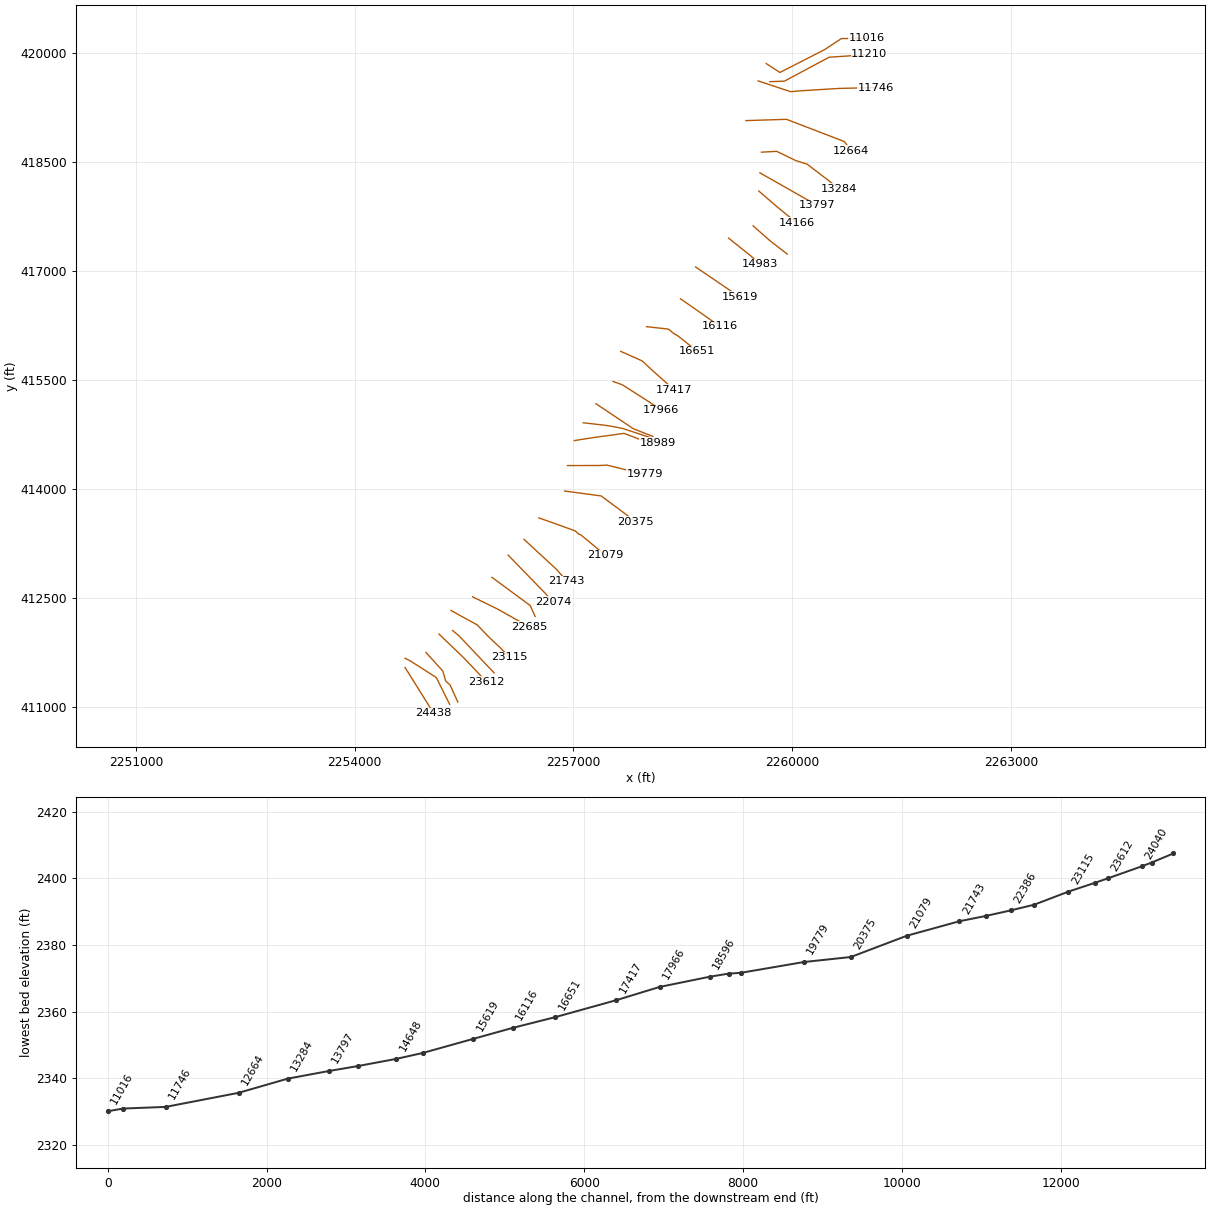
HEC-RAS study DOUTHTCK.prj: DOUTHTCK

--- DOUTHTCK.g01 (geometry) --- (continued)

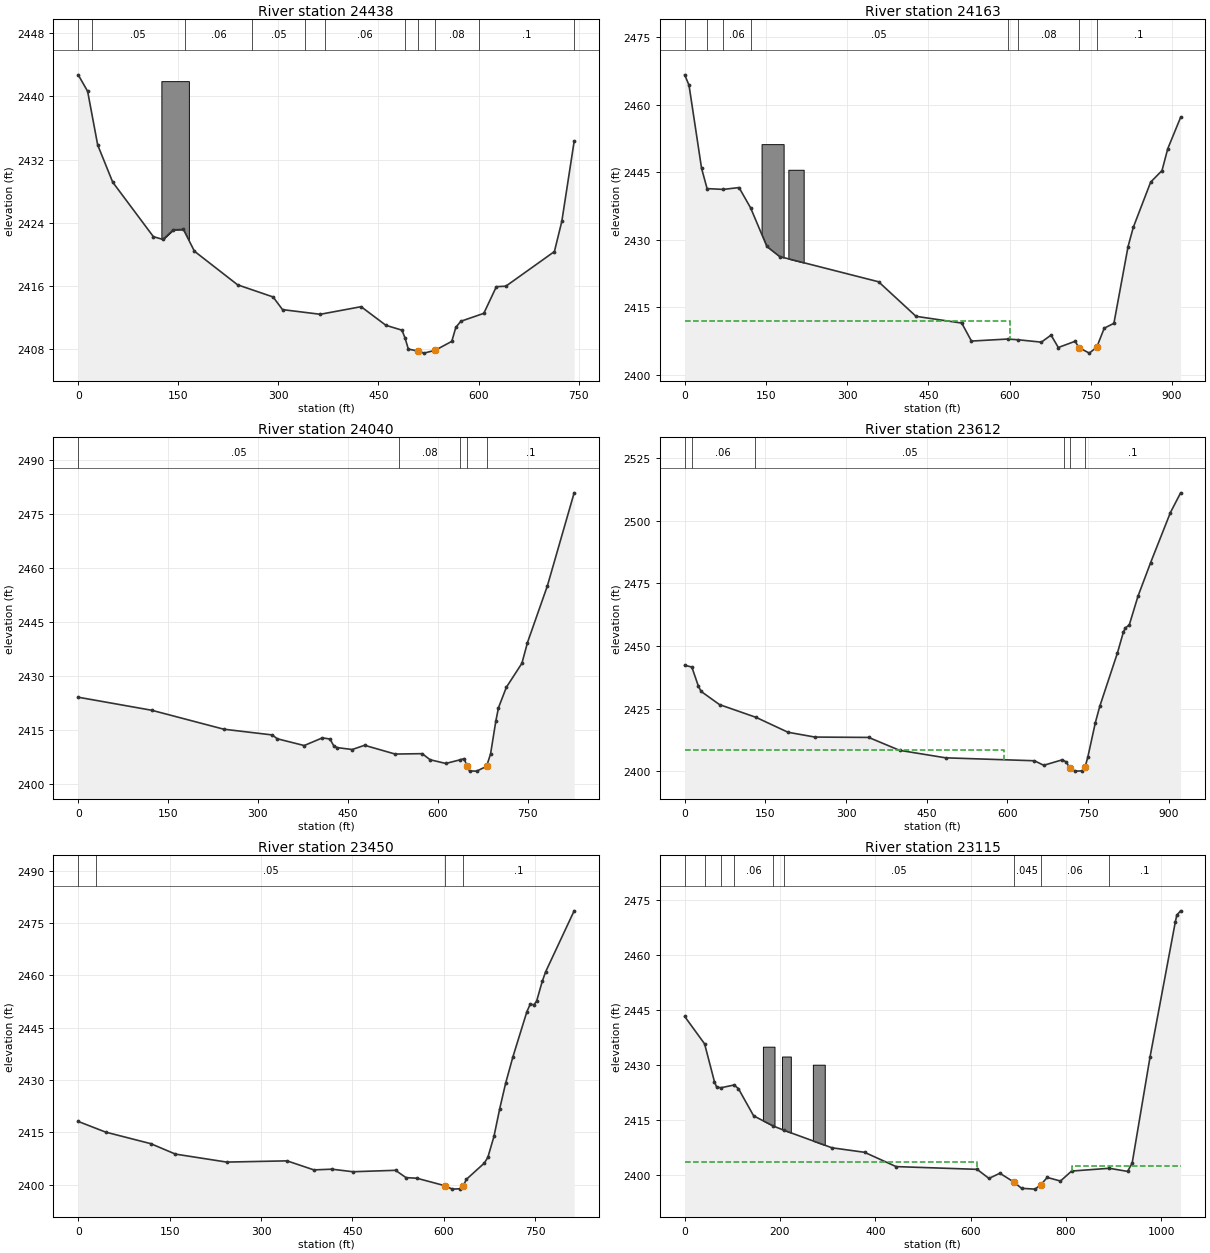
Type RM Length L Ch R = 1 ,24438   ,275.3,275,271.4
XS GIS Cut Line= 2
  2254692.714879411545.0090823852255085.96511774410914.301031757
#Sta/Elev= 30
       0 2442.71    14.1 2440.63    29.2 2433.84    51.7 2429.14   112.7 2422.25
   127.1  2421.9   142.6 2423.12   157.7 2423.16   174.2 2420.41     239 2416.16
   292.1 2414.63   306.2 2413.03   362.8 2412.44     424  2413.4   461.1 2411.05
   485.3 2410.43     490  2409.4   494.8 2408.04   508.9  2407.8   518.3 2407.53
   535.42407.904   559.9 2409.02     566  2410.8   573.6 2411.56   607.9 2412.56
   626.7 2415.93   640.9 2415.99   713.7 2420.37   724.8 2424.18   743.3  2434.3
#Mann= 11 ,-1,0
       0     .06       0      20     .05       0     160     .06       0
     260     .05       0     340      .1       0     370     .06       0
     490     .08       0   508.9    .045       0   535.4     .08       0
     600      .1       0   743.3     .12       0
#Block Obstruct= 1 ,-1
  124.65  165.86 2441.91
Bank Sta=508.9,535.4
XS Rating Curve= 0 ,0
Exp/Cntr(USF)=0,0
Exp/Cntr=0.3,0.1

Type RM Length L Ch R = 1 ,24163   ,123.8,123.3,122.5
XS GIS Cut Line= 5
2254692.22081439  411672.75642822254762.05356781411638.038663088
2255094.14336824411425.2456580422255121.33049527411406.647866582
2255303.86709371411038.830922792
#Sta/Elev= 30
       0 2466.64       8 2464.34    31.2 2445.85    41.4 2441.35    71.3 2441.17
   100.4 2441.58   121.8 2437.06   151.8 2428.49   175.5 2426.24   358.1 2420.64
   427.3 2412.96   511.7 2411.46   529.7 2407.46   596.3 2407.91     616 2407.75
   658.8 2407.22   676.7 2408.79   690.1 2406.03   721.3 2407.42   727.9 2406.03
   747.3 2404.78   761.12406.098   774.9 2410.32   792.8 2411.41   818.9 2428.45
   828.5 2432.72   860.7  2442.8   881.6 2445.36   892.3 2450.23     916 2457.19
#Mann= 8 ,-1,0
       0     .06       0    41.4    .016       0    71.3     .06       0
   121.8     .05       0   596.3      .1       0     616     .08       0
   727.9    .045       0   761.1      .1       0
#XS Ineff= 2 , 0
          600.39 2411.95
Permanent Ineff=
       F       F
#Block Obstruct= 2 ,-1
  141.99  182.74 2451.23   191.5  219.76 2445.54
Bank Sta=727.9,761.1
XS Rating Curve= 0 ,0
Exp/Cntr(USF)=0,0
Exp/Cntr=0.3,0.1

Type RM Length L Ch R = 1 ,24040   ,400.9,428.1,438
XS GIS Cut Line= 6
2254979.17192192411753.5699118762255209.09139057411498.522632439
2255232.96281082411421.8828095542255248.03949729411361.576063677
 2255309.6026337411306.2948799572255416.39582952411070.093458606
#Sta/Elev= 30
       0 2424.14   122.8 2420.52   242.9 2415.28   323.7 2413.69   332.4 2412.62
   377.2 2410.75   407.6 2412.88   420.2 2412.55   426.9 2410.57   432.6 2410.17
   457.4 2409.65     478 2410.82     529 2408.39   574.2  2408.5   587.3 2406.82
   613.6 2405.78   637.9 2406.82   644.4 2407.13   648.8    2405   653.2 2403.71
   665.1 2403.66   681.6 2404.99   688.3 2408.44   697.1 2417.56   701.5 2421.22
   714.6 2426.88   740.6 2433.54   749.9 2439.29     783 2454.93   827.8 2480.77
#Mann= 5 ,-1,0
       0     .05       0  535.82     .08       0   637.9      .1       0
   648.8    .045       0   681.6      .1       0
Bank Sta=648.8,681.6
XS Rating Curve= 0 ,0
Exp/Cntr(USF)=0,0
Exp/Cntr=0.3,0.1

Type RM Length L Ch R = 1 ,23612   ,165.9,161.3,162
XS GIS Cut Line= 5
2255157.80727646412006.4400054652255493.70175493411682.846006863
2255603.80092245411567.4668306522255702.15185258411462.883332912
 2255806.3111341411351.310838902
#Sta/Elev= 30
       0 2442.29    13.3 2441.61    25.5 2433.95    30.6 2431.86    64.8  2426.6
   132.7 2421.51   192.1 2415.56   242.1 2413.64   342.1  2413.5   399.6 2408.34
   485.3 2405.35   650.4 2404.18   667.5 2402.37   702.3 2404.57   709.8 2403.63
   715.5 2401.35   725.7 2400.04   738.1 2400.13   744.3 2401.62   749.5 2405.58
   763.6 2419.44   771.8 2425.94   804.6 2447.22   815.6  2455.5   819.3 2457.25
   826.5 2458.33   842.8 2469.86   866.2 2483.23   903.1 2503.28922.0903 2511.16
#Mann= 6 ,-1,0
       0    .016       0    13.3     .06       0     130     .05       0
  705.89      .1       0   715.5    .045       0   744.3      .1       0
#XS Ineff= 2 , 0
          593.24 2408.59
Permanent Ineff=
       F       F
Bank Sta=715.5,744.3
XS Rating Curve= 0 ,0
Exp/Cntr(USF)=0,0
Exp/Cntr=0.3,0.1

Type RM Length L Ch R = 1 ,23450   ,312.3,334.9,312.1
XS GIS Cut Line= 3
2255345.80585123 412054.703617822255434.00446708411980.074019797
 2255913.4430968411472.366602947
#Sta/Elev= 30
       0 2418.13      45 2415.07   119.1 2411.75   159.5 2408.76   243.6 2406.47
   342.7 2406.82   386.7 2404.23   416.2 2404.43   450.8  2403.7   520.7 2404.11
   537.9 2402.01   555.6 2401.84   602.3 2399.66   613.9 2398.71   625.7 2398.81
   632.1 2399.75   636.9 2401.51   666.3 2406.16   672.2 2407.83   682.2 2413.83
   691.7 2421.81   701.3 2429.04   713.3 2436.66   736.3 2449.65   741.6 2451.72
   747.9 2451.62   752.2 2452.63   761.4 2458.29   767.1  2461.1   813.8 2478.55
#Mann= 4 ,-1,0
       0     .06       0      30     .05       0   602.3    .045       0
   632.1      .1       0
Bank Sta=602.3,632.1
XS Rating Curve= 0 ,0
Exp/Cntr(USF)=0,0
Exp/Cntr=0.3,0.1

Type RM Length L Ch R = 1 ,23115   ,426.9,430.1,437.9
XS GIS Cut Line= 6
2255321.44072811412331.2811615982255682.54281202412132.332351971
2255813.55476537411994.240363217 2255902.5856753411907.148402034
2255992.86335652411822.6489662022256126.34418138411687.551840697
#Sta/Elev= 30
       0 2443.27    41.8 2435.78    62.5 2425.42    67.1 2423.96    76.2 2423.78
   103.7 2424.53   112.7 2423.55   144.7  2416.1   185.8 2413.32   208.6 2412.14
   309.1 2407.36   377.4 2406.13   443.7 2402.22   613.7 2401.47   638.5 2398.99
   661.4  2400.4   690.2 2398.05     707 2396.28   735.4 2396.06   747.6 2397.29
   760.8 2399.26   788.6 2398.27     812    2401     891 2401.76   929.5 2400.91
   939.1  2403.2   976.6  2432.2  1029.6  2469.1  1032.8 2470.991040.747 2472.15
#Mann= 9 ,-1,0
       0      .1       0    41.8     .07       0    76.2    .016       0
   103.7     .06       0   185.8    .016       0   208.6     .05       0
   690.2    .045       0   747.6     .06       0     891      .1       0
#XS Ineff= 2 , 0
           612.6 2403.41  811.94         2402.49
Permanent Ineff=
       F       F
#Block Obstruct= 3 ,-1
  164.15  188.49 2435.01  204.32  222.73 2432.32  268.97  293.92 2430.08
Bank Sta=690.2,747.6
XS Rating Curve= 0 ,0
Exp/Cntr(USF)=0,0
Exp/Cntr=0.3,0.1

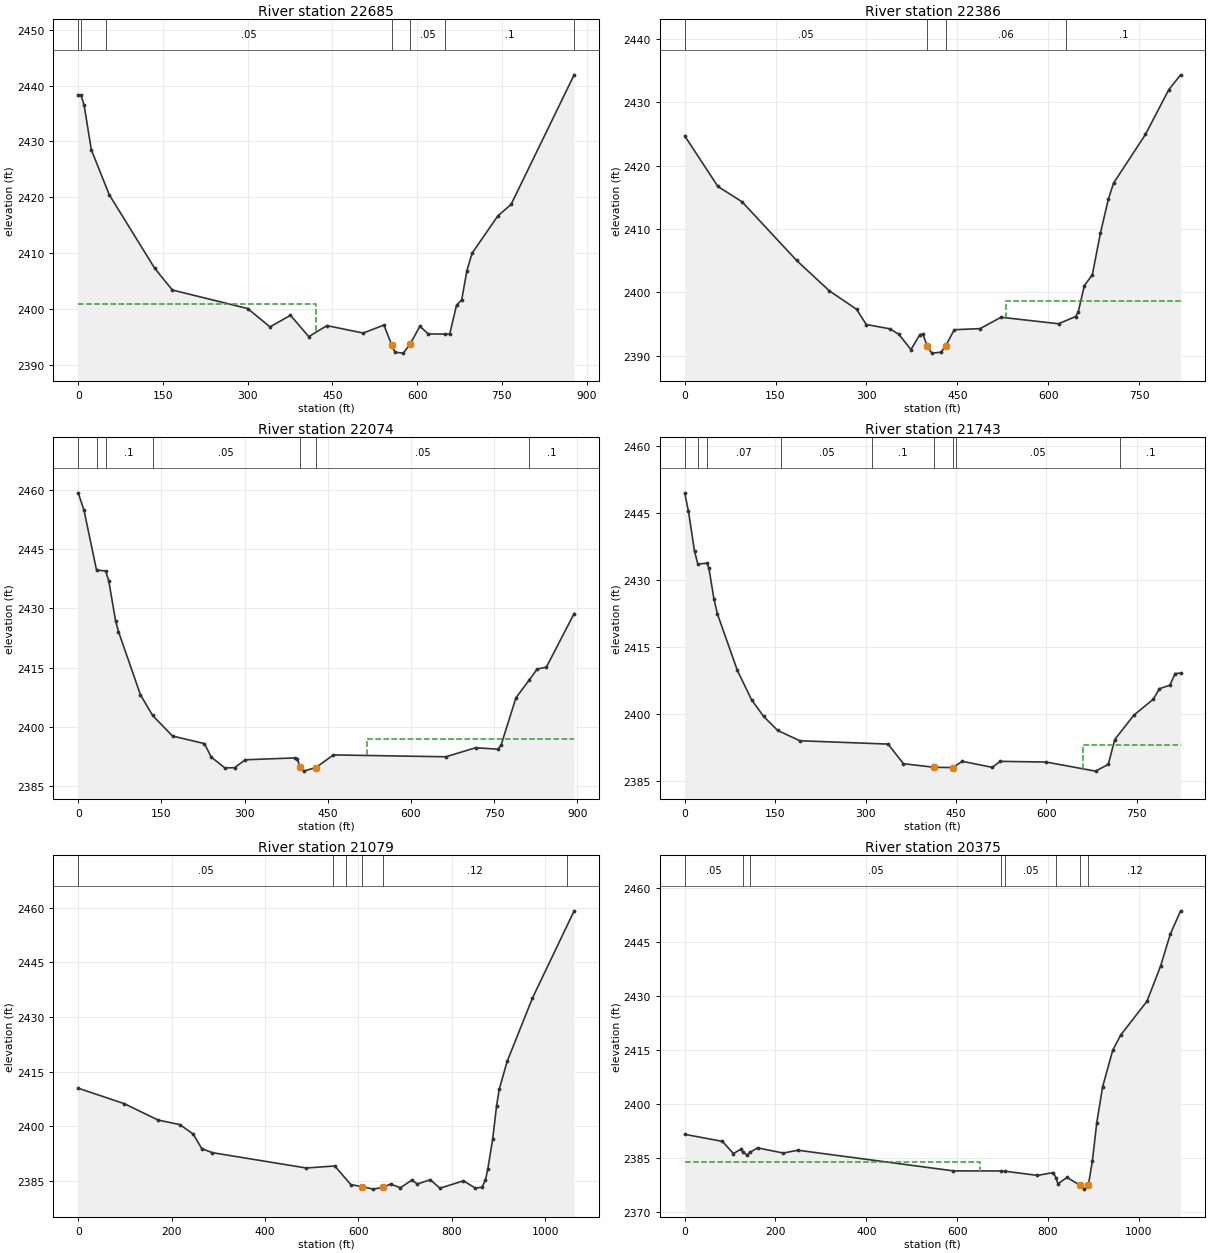
Type RM Length L Ch R = 1 ,22685   ,302.7,298.9,288.8
XS GIS Cut Line= 4
2255618.75690179412518.7698493532255953.57586326 412354.43093517
2256237.00909051412194.8501949582256393.14818831412105.888331757
#Sta/Elev= 30
       0 2438.29     5.2 2438.23    10.5 2436.46    23.2 2428.52      55 2420.46
   135.3 2407.33   166.6 2403.43   300.1 2400.11   339.5 2396.83   375.8 2398.91
   408.1 2395.09   440.2 2397.06   504.5 2395.73   541.2 2397.16     555  2393.6
     555 2393.59   560.8  2392.3   575.5 2392.14   587.5 2393.76   604.9 2396.95
   619.6 2395.58   649.6 2395.54   657.7 2395.58   669.7 2400.71   678.9 2401.68
   688.1 2406.89   697.3 2410.02   742.9 2416.69   766.3 2418.74  877.95 2441.92
#Mann= 7 ,-1,0
       0    .016       0     5.2     .06       0      50     .05       0
     555    .045       0   587.5     .05       0   649.6      .1       0
  877.95     .12       0
#XS Ineff= 2 , 0
          420.27 2400.98
Permanent Ineff=
       F       F
Bank Sta=555,587.5
XS Rating Curve= 0 ,0
Exp/Cntr(USF)=0,0
Exp/Cntr=0.3,0.1

Type RM Length L Ch R = 1 ,22386   ,323.9,312.3,298
XS GIS Cut Line= 3
2255884.04355818412787.430580223 2256409.8429988412398.452069317
2256476.55733642412248.062121787
#Sta/Elev= 30
       0 2424.68    54.9 2416.69    94.7 2414.28   184.7 2405.03     239 2400.22
   283.8 2397.32   299.7 2394.92   338.5 2394.25   353.5 2393.38   373.5 2390.97
   388.3 2393.34   393.2 2393.39   400.6 2391.48   407.8 2390.41   423.1 2390.55
   430.7 2391.53     445  2394.1   487.8 2394.28   522.2 2396.07   617.1 2395.04
   645.2 2396.18   649.5 2396.87   659.8 2401.07   672.9 2402.77   686.1 2409.28
   699.2 2414.64   707.9 2417.22   760.5 2424.89   799.2 2431.98   818.6  2434.3
#Mann= 4 ,-1,0
       0     .05       0   400.6    .045       0   430.7     .06       0
     630      .1       0
#XS Ineff= 2 , 0
                          530.14         2398.67
Permanent Ineff=
       F       F
Bank Sta=400.6,430.7
XS Rating Curve= 0 ,0
Exp/Cntr(USF)=0,0
Exp/Cntr=0.3,0.1

Type RM Length L Ch R = 1 ,22074   ,331.3,331.1,345.1
XS GIS Cut Line= 3
2256105.81893619413093.5455192582256594.82895786412588.547499864
2256725.24103949412448.425848571
#Sta/Elev= 30
       0 2459.34    10.4 2454.95      33 2439.76    49.4 2439.52    55.1    2437
    67.3 2426.95    72.6 2424.16   112.2 2408.13   134.1 2402.88   170.1 2397.65
   227.6 2395.73   239.9 2392.32   264.3 2389.58     282 2389.62   301.2 2391.63
   390.3  2392.1   395.1 2391.82  399.99 2389.82   406.4 2388.75   428.9 2389.67
   460.2 2392.86   663.1 2392.39   716.7 2394.68   757.2 2394.32   762.9  2395.5
   789.5 2407.37   813.8 2411.94   827.8 2414.65   844.2 2415.11894.3801 2428.73
#Mann= 7 ,-1,0
       0      .1       0      33    .016       0    49.4      .1       0
   134.1     .05       0  399.99    .045       0   428.9     .05       0
   813.8      .1       0
#XS Ineff= 2 , 0
                          519.93         2396.99
Permanent Ineff=
       F       F
Bank Sta=399.99,428.9
XS Rating Curve= 0 ,0
Exp/Cntr(USF)=0,0
Exp/Cntr=0.3,0.1

Type RM Length L Ch R = 1 ,21743   ,581,663.7,604.5
XS GIS Cut Line= 4
2256324.11062279413309.9858862262256766.09108051 412900.49772861
2256877.62543471412773.5961982952256910.38505174412734.238380683
#Sta/Elev= 30
       0 2449.44     6.3 2445.29    16.4 2436.32    21.9  2433.5    37.4  2433.7
    40.2 2432.54    48.7 2425.59    54.4 2422.31    87.3 2409.74     111 2403.13
   130.8 2399.44   154.2 2396.28   190.9 2393.97   337.4 2393.22   362.9 2388.83
   413.9 2388.03     445 2387.96   460.3 2389.37   510.1 2388.02   523.6 2389.36
   599.9  2389.2   681.5 2387.17   702.7 2388.68   713.4 2394.24     745 2399.68
   777.2 2403.24   787.6 2405.62   804.8 2406.39   813.6 2409.01822.6746 2409.09
#Mann= 9 ,-1,0
       0      .1       0    21.9    .016       0    37.4     .07       0
     160     .05       0     310      .1       0   413.9    .045       0
     445      .1       0     450     .05       0  722.52      .1       0
#XS Ineff= 2 , 0
                             660          2393.1
Permanent Ineff=
       F       F
Bank Sta=413.9,445
XS Rating Curve= 0 ,0
Exp/Cntr(USF)=0,0
Exp/Cntr=0.3,0.1

Type RM Length L Ch R = 1 ,21079   ,682.4,704.4,615.1
XS GIS Cut Line= 6
  2256526.808711413605.945627799 2256735.7341268413532.301415213
2257021.43154293413428.5834586682257078.99874815 413380.16929499
   2257103.33632413372.0567710392257438.44964306413093.489591065
#Sta/Elev= 30
       0 2410.48    98.6 2406.24     171 2401.75   217.8  2400.5   246.2  2397.9
   264.5 2393.94   286.7 2392.82   488.6  2388.6   549.4 2389.16   583.8 2384.05
   607.2 2383.51   631.8 2382.81   653.5 2383.33   669.1 2384.21     690 2383.17
   714.2 2385.28   726.4 2384.22     754 2385.39   774.6 2383.06     825 2385.09
   850.5  2383.1   864.7 2383.33     872 2385.24   877.2 2388.34   887.5 2396.42
     896 2405.67   901.7 2410.22   918.6 2417.82   972.7 2435.17  1062.1 2459.11
#Mann= 6 ,-1,0
       0     .05       0  545.47      .1       0  573.36     .12       0
   607.2    .045       0   653.5     .12       0 1047.29      .1       0
Bank Sta=607.2,653.5
XS Rating Curve= 0 ,0
Exp/Cntr(USF)=0,0
Exp/Cntr=0.3,0.1

Type RM Length L Ch R = 1 ,20375   ,593.1,595.6,600.4
XS GIS Cut Line= 4
2256881.07726043413975.5480768382257381.68896611 413907.90901324
2257610.36875087413738.5605922592257851.14780675413555.518624932
#Sta/Elev= 30
       0 2391.65    83.1 2389.69   107.3  2386.3   124.2 2387.54   128.3 2386.77
   137.2 2385.89   144.4  2386.7   160.5 2387.89   217.1 2386.45   249.3 2387.23
   591.8  2381.5   695.8 2381.47   706.2 2381.39     777 2380.24   812.1 2381.03
   817.7 2379.48   822.1 2377.93   842.2 2379.67  869.89 2377.56   880.5 2376.43
     889 2377.54   897.8 2384.19   907.6 2394.92   920.4 2404.83   942.7 2414.98
   960.4 2419.24  1018.1 2428.58  1048.2  2438.4  1069.6 2447.27  1092.2 2453.69
#Mann= 8 ,-1,0
       0     .05       0   128.3    .045       0   144.4     .05       0
   695.8      .1       0   706.2     .05       0   817.7     .12       0
  869.89    .045       0     889     .12       0
#XS Ineff= 2 , 0
          651.06 2383.97
Permanent Ineff=
       F       F
Bank Sta=869.89,889
XS Rating Curve= 0 ,0
Exp/Cntr(USF)=0,0
Exp/Cntr=0.3,0.1

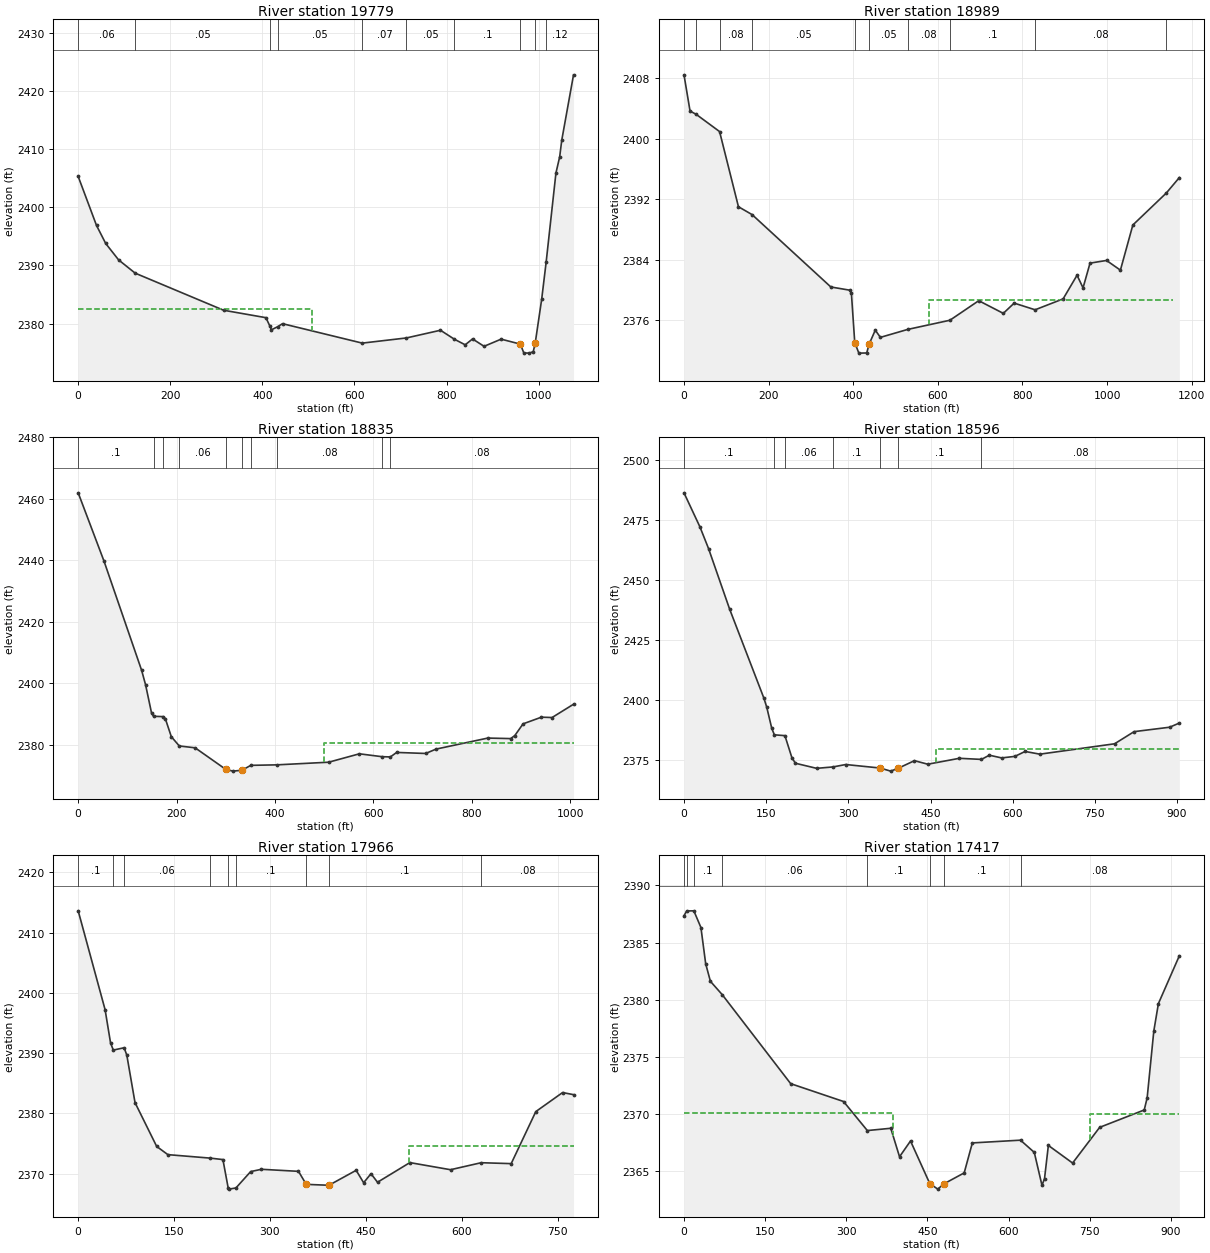
Type RM Length L Ch R = 1 ,19779   ,479.8,790,697.4
XS GIS Cut Line= 5
 2256920.3533369414326.3542137872257358.28241037414327.191663949
2257462.52276535414332.3125652222257698.76824833414273.690926054
2257981.31398338414207.635625015
#Sta/Elev= 30
       0 2405.27    39.8 2396.85    59.8 2393.75    87.8 2390.93   123.8 2388.65
   315.8 2382.28   407.8    2381   415.8 2379.65   419.8 2378.92   433.8 2379.47
   443.8 2379.97     617 2376.63     713 2377.52   786.9 2378.84   817.3 2377.29
   840.6 2376.34   856.6 2377.35   881.6 2376.08   918.6 2377.31   960.4 2376.46
   967.9 2374.95   979.9 2374.91   988.4 2375.16   992.62376.591  1006.7 2384.15
  1016.4 2390.52  1037.7 2405.86  1045.9 2408.67  1050.3 2411.49  1075.9 2422.73
#Mann= 10 ,-1,0
       0     .06       0   123.8     .05       0   415.8    .045       0
   433.8     .05       0     617     .07       0     713     .05       0
   817.3      .1       0   960.4    .045       0   992.6      .1       0
  1016.4     .12       0
#XS Ineff= 2 , 0
          508.39 2382.44
Permanent Ineff=
       F       F
Bank Sta=960.4,992.6
XS Rating Curve= 0 ,0
Exp/Cntr(USF)=0,0
Exp/Cntr=0.3,0.1

Type RM Length L Ch R = 1 ,18989   ,157.9,154.1,107.3
XS GIS Cut Line= 6
2257013.07956268414669.9539898282257307.99234762414716.248438627
2257486.31170595414740.2529676342257695.16523854414769.668609146
2257937.14605637 414676.946987362258156.72390893414642.520242392
#Sta/Elev= 30
       0 2408.41    14.3 2403.63    28.7  2403.2    84.1 2400.92   128.7    2391
     161 2389.96   347.1 2380.41   391.5 2379.99   395.6 2379.65   403.6 2373.07
   413.3 2371.68   431.9  2371.7   437.6 2372.87   452.1 2374.71   464.2 2373.76
   528.8 2374.81   628.5 2376.02   696.7  2378.6   754.7 2376.93   780.4 2378.28
   829.9  2377.4   896.1 2378.84     929 2381.96   943.2 2380.29   959.7 2383.56
   998.7 2383.91  1031.5 2382.63  1060.9 2388.59    1140 2392.81  1170.8 2394.85
#Mann= 10 ,-1,0
       0     .08       0    28.7    .016       0    84.1     .08       0
     161     .05       0   403.6    .045       0   437.6     .05       0
   528.8     .08       0   628.5      .1       0   829.9     .08       0
    1140      .1       0
#XS Ineff= 1 ,-1
  578.031155.951 2378.64
Permanent Ineff=
       F
Bank Sta=403.6,437.6
XS Rating Curve= 0 ,0
Exp/Cntr(USF)=0,0
Exp/Cntr=0.3,0.1

Type RM Length L Ch R = 1 ,18835   ,189.1,239.5,103.4
XS GIS Cut Line= 5
2257136.03783627414915.327311486 2257419.9557329414883.063914142
2257516.74592493414868.5453853372257668.38389245414839.508327728
2258113.61877579414692.709869812
#Sta/Elev= 30
       0 2461.93    52.5 2439.72     129 2404.19     137  2399.5   149.1 2390.34
   153.1 2389.27   173.2 2389.16   177.3 2388.41   189.3 2382.64   205.5 2379.62
   237.7 2379.02   299.72372.044   314.3 2371.44   332.72371.718   350.9 2373.32
   403.8 2373.48   509.1 2374.34   571.5 2377.07   617.8 2376.13   634.6 2376.06
   647.3 2377.52   706.3 2377.18   727.3  2378.6   832.6 2382.19   878.9 2382.02
   887.4 2382.99   904.2 2386.81   941.5 2388.98   963.2 2388.87  1006.8 2393.19
#Mann= 10 ,-1,0
       0      .1       0   153.1    .016       0   173.2     .08       0
   205.5     .06       0   299.7    .045       0   332.7      .1       0
   350.9     .05       0   403.8     .08       0   617.8    .045       0
   634.6     .08       0
#XS Ineff= 2 , 0
                             500         2380.65
Permanent Ineff=
       F       F
Bank Sta=299.7,332.7
XS Rating Curve= 0 ,0
Exp/Cntr(USF)=0,0
Exp/Cntr=0.3,0.1

Type RM Length L Ch R = 1 ,18596   ,427.6,629.8,447.6
XS GIS Cut Line= 4
2257310.93968623 415177.370779742257445.32183939415087.784478882
2257823.82337744414832.7110219612258090.22968796414728.243517553
#Sta/Elev= 30
       0 2486.37    29.2 2472.13    44.8 2463.16    83.2    2438   145.7 2400.96
     151 2397.14   160.1 2388.39   164.9 2385.62   184.2 2385.27   197.1 2375.97
   203.5 2373.77   242.1 2371.66   272.1 2372.25   295.2 2373.25   357.9 2371.79
   377.2  2370.5   390.2 2371.61   420.6 2374.85     445 2373.38   502.6 2375.84
   542.9 2375.38   557.3 2377.13   579.8    2376   603.9 2376.64   622.6 2378.69
   649.5 2377.56   785.9 2381.88   821.5 2386.94   886.4 2388.78   904.1 2390.52
#Mann= 7 ,-1,0
       0      .1       0   164.9    .016       0   184.2     .06       0
   272.1      .1       0   357.9    .045       0   390.2      .1       0
   542.9     .08       0
#XS Ineff= 2 , 0
                             460          2379.7
Permanent Ineff=
       F       F
Bank Sta=357.9,390.2
XS Rating Curve= 0 ,0
Exp/Cntr(USF)=0,0
Exp/Cntr=0.3,0.1

Type RM Length L Ch R = 1 ,17966   ,464,549.3,367.7
XS GIS Cut Line= 4
2257544.48779637 415484.267391172257672.01027841415438.753483356
2258037.94277419415204.2218632862258206.18966914415087.546422955
#Sta/Elev= 30
       0  2413.6    42.1  2397.2    50.6 2391.71    54.9  2390.5    71.9 2390.89
    76.1 2389.64    88.9 2381.79   122.8 2374.52   140.3 2373.16   206.9 2372.58
   226.4 2372.34   234.7 2367.59   235.4 2367.44   246.7 2367.63   269.8 2370.35
   286.6 2370.73   344.6 2370.39   356.7 2368.23   392.2 2368.08   434.8 2370.56
   446.5  2368.5     458    2370   468.2 2368.58   518.8 2371.84   582.4 2370.66
   630.3 2371.82   677.3 2371.67   715.8  2380.3   757.7 2383.46   774.8 2383.11
#Mann= 9 ,-1,0
       0      .1       0    54.9    .016       0    71.9     .06       0
   206.9      .1       0   234.7    .045       0   246.7      .1       0
   356.7    .045       0   392.2      .1       0   630.3     .08       0
#XS Ineff= 2 , 0
                          517.86         2374.62
Permanent Ineff=
       F       F
Bank Sta=356.7,392.2
XS Rating Curve= 0 ,0
Exp/Cntr(USF)=0,0
Exp/Cntr=0.3,0.1

Type RM Length L Ch R = 1 ,17417   ,584.7,765.9,615.6
XS GIS Cut Line= 4
2257651.56696611415897.971409755 2257942.7998138415768.122170569
2258149.64441423415577.274585138 2258384.5002644415366.926006378
#Sta/Elev= 30
       0 2387.34       5 2387.76    18.2 2387.77    31.3 2386.31    40.1 2383.14
    48.8 2381.61    70.7 2380.44   197.2 2372.66   294.9  2371.1   338.9 2368.56
   382.2 2368.76   398.4 2366.27   418.7 2367.65   454.32363.927   469.1 2363.44
   480.4  2363.9   517.9 2364.86     533 2367.48     622 2367.72   647.5 2366.65
   661.7 2363.77   666.4 2364.36   673.5 2367.26   718.3 2365.72   768.3 2368.84
   850.7 2370.36   856.1 2371.42   868.4 2377.26   876.9 2379.66   915.6 2383.84
#Mann= 8 ,-1,0
       0      .1       0       5    .016       0    18.2      .1       0
    70.7     .06       0   338.9      .1       0   454.3    .045       0
   480.4      .1       0     622     .08       0
#XS Ineff= 2 , 0
          386.48 2370.06  750.42         2370.03
Permanent Ineff=
       F       F
Bank Sta=454.3,480.4
XS Rating Curve= 0 ,0
Exp/Cntr(USF)=0,0
Exp/Cntr=0.3,0.1

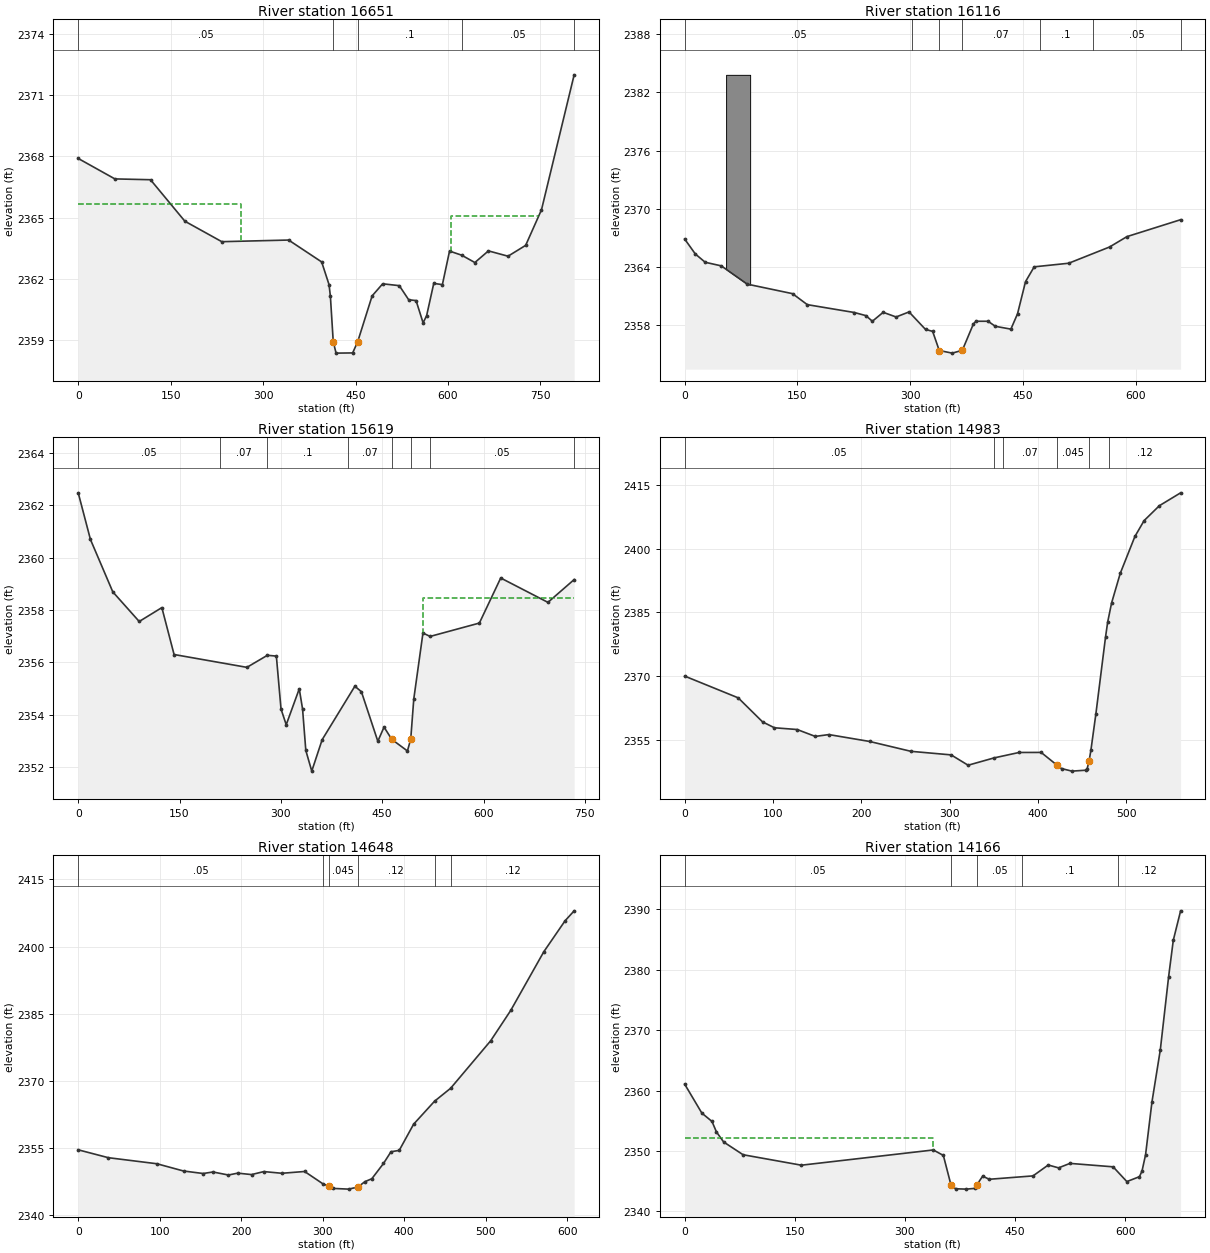
Type RM Length L Ch R = 1 ,16651   ,460,534.6,450.4
XS GIS Cut Line= 6
2258004.19167814416238.9614033042258303.28600764416205.090479514
2258379.79036775416142.7968227692258428.59739893416115.793494274
2258533.51920276416033.5078940262258701.37413398415897.759776213
#Sta/Elev= 30
       0 2367.89    59.5 2366.89   117.3 2366.85   173.1 2364.82     233 2363.82
   341.4  2363.9     395 2362.83     407 2361.72   409.2 2361.14   413.8 2358.93
   418.4 2358.37   445.3 2358.38   453.42358.921   476.9 2361.17     494 2361.76
     521 2361.67   536.2 2360.98   548.2 2360.94   559.6 2359.85   565.3  2360.2
   576.9 2361.78   590.9 2361.72   602.5 2363.36   622.2 2363.16   643.6  2362.8
   665.6 2363.37   697.4 2363.11     726 2363.64   751.7 2365.38   804.7 2371.98
#Mann= 5 ,-1,0
       0     .05       0   413.8    .045       0   453.4      .1       0
   622.2     .05       0   804.7      .1       0
#XS Ineff= 2 ,-1
       0  263.66 2365.68  604.85747.6062 2365.07
Permanent Ineff=
       F       F
Bank Sta=413.8,453.4
XS Rating Curve= 0 ,0
Exp/Cntr(USF)=0,0
Exp/Cntr=0.3,0.1

Type RM Length L Ch R = 1 ,16116   ,490.1,497.4,487.2
XS GIS Cut Line= 4
2258469.81759426416622.5946821532258575.74828225416548.727210688
2258701.30241619416460.4209012232259009.49315658416242.969669432
#Sta/Elev= 30
       0 2366.89    14.2 2365.35    27.3  2364.5    48.7 2364.13    83.2 2362.25
   143.5 2361.27   163.1 2360.14   225.7 2359.33   241.1 2359.01   249.7 2358.43
   264.1 2359.35   281.3 2358.87   298.5 2359.39   320.4 2357.59   329.9 2357.39
   338.7 2355.42   355.9 2355.15   369.4 2355.44   384.1 2358.15   387.5 2358.43
   403.6 2358.43   413.3 2357.91     434 2357.62   442.8 2359.19   453.5 2362.51
     465 2364.03   510.9  2364.4   565.2 2366.07   588.4 2367.14   659.8 2368.88
#Mann= 7 ,-1,0
       0     .05       0  302.64     .07       0   338.7    .045       0
   369.4     .07       0  472.64      .1       0  542.64     .05       0
  659.82      .1       0
#Block Obstruct= 1 ,-1
   55.11    87.1 2383.79
Bank Sta=338.7,369.4
XS Rating Curve= 0 ,0
Exp/Cntr(USF)=0,0
Exp/Cntr=0.3,0.1

Type RM Length L Ch R = 1 ,15619   ,574.2,635.7,576.7
XS GIS Cut Line= 2
2258677.90832879417060.080619781 2259284.2366606416646.211768885
#Sta/Elev= 30
       0 2362.47    18.1 2360.69    51.2 2358.69    90.3 2357.56   123.8 2358.09
   141.9  2356.3   249.7 2355.81     280 2356.27   293.3 2356.24   300.2 2354.22
   307.9 2353.62   327.2 2354.99   332.1 2354.22   336.9 2352.64   345.7 2351.85
   361.1 2353.05   409.5 2355.09   419.2 2354.88   443.5 2352.99   452.7 2353.53
   464.2 2353.06   487.3 2352.62   492.2 2353.07   496.7  2354.6   510.3 2357.12
   520.9 2356.99   593.8  2357.5   625.4 2359.22   695.3 2358.29   734.1 2359.16
#Mann= 8 ,-1,0
       0     .05       0     210     .07       0     280      .1       0
     400     .07       0   464.2    .045       0   492.2     .07       0
   520.9     .05       0   734.1      .1       0
#XS Ineff= 2 , 0
                           510.2         2358.44
Permanent Ineff=
       F       F
Bank Sta=464.2,492.2
XS Rating Curve= 0 ,0
Exp/Cntr(USF)=0,0
Exp/Cntr=0.3,0.1

Type RM Length L Ch R = 1 ,14983   ,342.4,334.8,337.1
XS GIS Cut Line= 3
 2259128.9073337417457.9085730412259440.96621079417207.575627685
2259557.55963739417096.126028725
#Sta/Elev= 30
       0 2369.98    60.6 2364.86    88.2  2359.2   101.6 2357.82   127.3 2357.41
   147.8 2355.79   163.2 2356.22   209.3  2354.6   256.1 2352.28   301.6 2351.44
   320.8 2349.01     350 2350.72   378.5 2352.01   403.5 2352.02   420.9 2349.11
   426.6 2348.22   438.3 2347.62   454.3 2347.84   455.6 2348.21   457.8 2350.07
   459.8 2352.53   465.4 2361.02   476.4 2379.23   478.8  2382.7   483.2 2387.17
     493 2394.14   509.6 2402.83     520 2406.56   537.3 2410.07 561.351  2413.1
#Mann= 6 ,-1,0
       0     .05       0     350      .1       0     360     .07       0
   420.9    .045       0   457.8     .07       0  480.06     .12       0
Bank Sta=420.9,457.8
XS Rating Curve= 0 ,0
Exp/Cntr(USF)=0,0
Exp/Cntr=0.3,0.1

Type RM Length L Ch R = 1 ,14648   ,435.6,481.8,432
XS GIS Cut Line= 3
2259465.60545841 417626.802629632259694.23510645417424.462040949
2259933.66145374417238.332806804
#Sta/Elev= 30
       0 2354.62      37 2352.86    96.5 2351.51   129.2 2349.89   153.3 2349.33
   165.4 2349.67   184.3 2348.99   195.7 2349.41   212.7 2349.09   227.8 2349.76
   249.9 2349.38   277.8 2349.78   300.5    2347   307.7 2346.51   312.8    2346
   331.8 2345.84   343.2 2346.31   351.8 2347.51   360.3 2348.16   374.6 2351.57
   383.8 2354.19   393.9 2354.49   411.6 2360.35   437.3 2365.48     457 2368.37
   506.2 2378.99   530.7 2385.74   571.3 2398.85   597.4 2405.77608.5724    2408
#Mann= 6 ,-1,0
       0     .05       0   300.5      .1       0   307.7    .045       0
   343.2     .12       0   437.3      .1       0     457     .12       0
Bank Sta=307.7,343.2
XS Rating Curve= 0 ,0
Exp/Cntr(USF)=0,0
Exp/Cntr=0.3,0.1

Type RM Length L Ch R = 1 ,14166   ,306.2,368.9,334.7
XS GIS Cut Line= 3
2259544.06318011418106.0785826512259793.49899201417889.857317525
2260060.81867669417670.879851645
#Sta/Elev= 30
       0 2361.06    23.4 2356.27    37.2 2354.89    43.3 2353.15    53.1 2351.49
    79.6 2349.38     159 2347.65   338.7 2350.17   352.4 2349.27   362.7 2344.43
     369 2343.75   383.7 2343.69     395 2343.81   397.9 2344.37     406 2345.84
   414.9 2345.32   474.6 2345.88   495.3 2347.68   509.4 2347.21   524.9 2347.95
   583.7 2347.38   602.4 2344.94   619.6 2345.75   623.1  2346.7   627.9 2349.37
   636.6  2358.1     648 2366.74   659.3 2378.82   665.7 2384.88675.6647 2389.74
#Mann= 5 ,-1,0
       0     .05       0   362.7    .045       0   397.9     .05       0
  460.11      .1       0  590.11     .12       0
#XS Ineff= 2 , 0
          337.97 2352.19
Permanent Ineff=
       F       F
Bank Sta=362.7,397.9
XS Rating Curve= 0 ,0
Exp/Cntr(USF)=0,0
Exp/Cntr=0.3,0.1

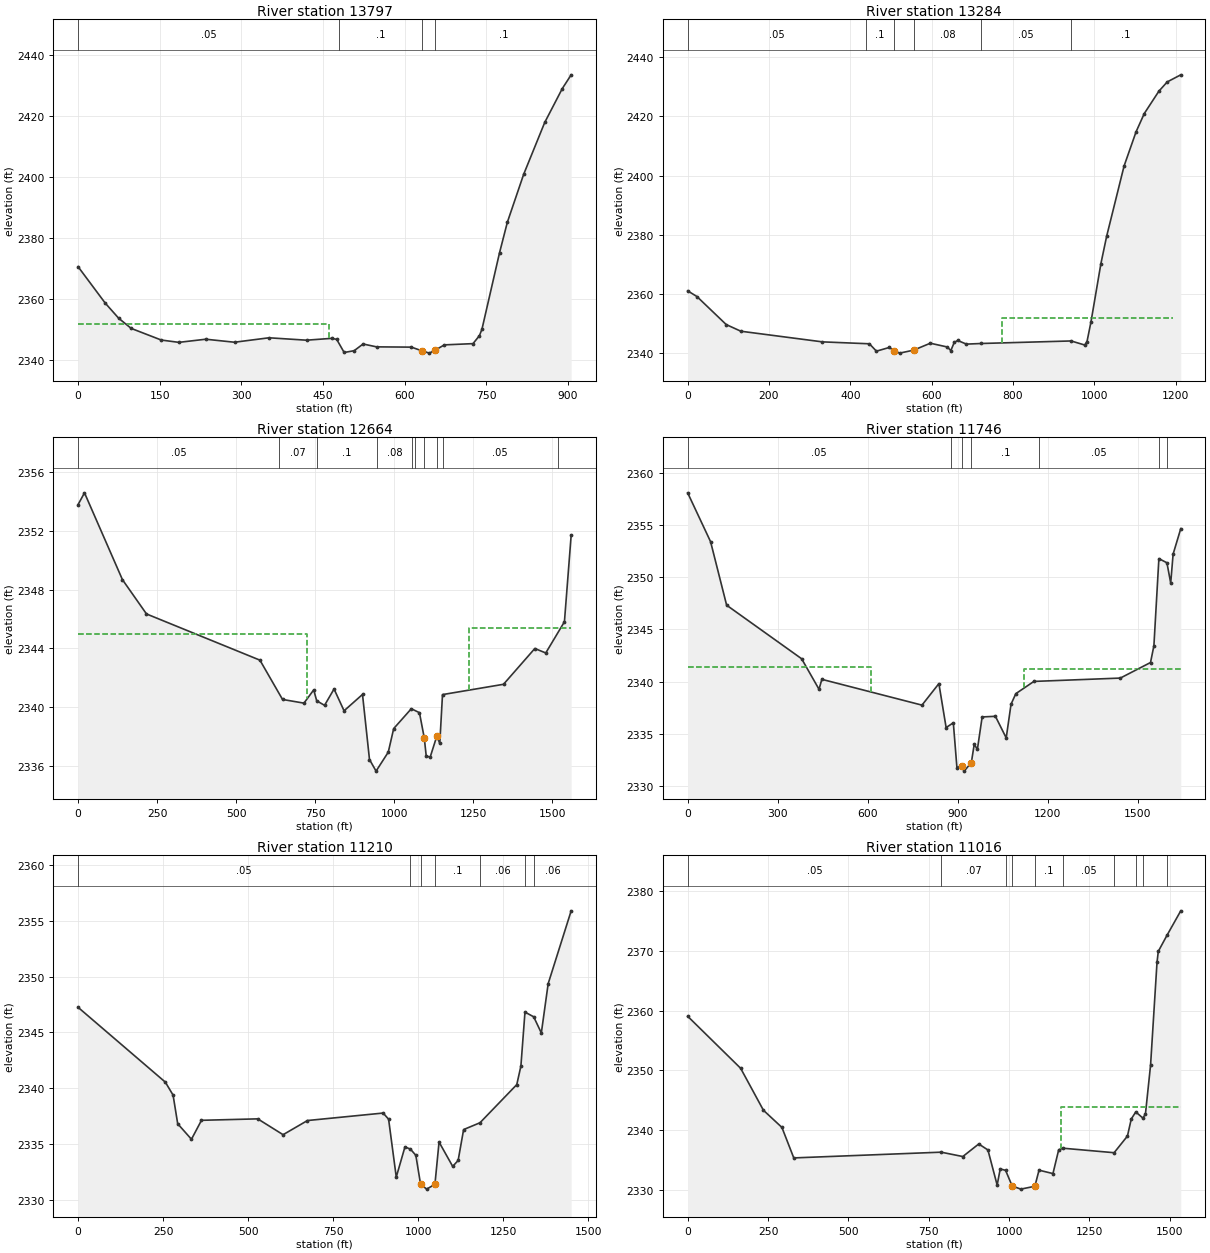
Type RM Length L Ch R = 1 ,13797   ,429.7,513.6,430.6
XS GIS Cut Line= 3
2259559.27424661 418356.363801582260188.53582843417998.010475693
2260346.27987619 417907.13618731
#Sta/Elev= 30
       0  2370.6    49.9 2358.63    74.7 2353.64    97.7 2350.31   152.9 2346.49
   185.2 2345.73   234.7 2346.76   287.5 2345.77   350.9 2347.23   419.9 2346.44
   466.4 2347.05   475.3 2346.71     489  2342.4   507.4 2342.99   523.8 2345.19
   548.5 2344.25   612.7 2344.16   631.7 2342.95   645.5 2342.19   656.8 2343.21
   673.1  2344.9   725.8 2345.31   737.6 2347.93   742.2 2350.02   774.5 2375.14
   788.9 2385.19   818.9 2400.95   857.6 2417.99   889.9 2429.13906.1935 2433.64
#Mann= 4 ,-1,0
       0     .05       0     480      .1       0   631.7    .045       0
   656.8      .1       0
#XS Ineff= 2 , 0
          461.41 2351.68
Permanent Ineff=
       F       F
Bank Sta=631.7,656.8
XS Rating Curve= 0 ,0
Exp/Cntr(USF)=0,0
Exp/Cntr=0.3,0.1

Type RM Length L Ch R = 1 ,13284   ,483.9,619.5,522.6
XS GIS Cut Line= 6
2259581.43245431418641.2053153842259789.33187563418652.642311231
2260048.83934148418526.4504454842260145.91285423418495.381212071
   2260207.59685 418475.56662865 2260643.2943453418140.931723768
#Sta/Elev= 30
       0    2361    22.8 2359.07    94.9 2349.58   130.9 2347.33   331.5 2343.73
   447.1 2343.08   464.3 2340.58     496 2341.84   506.8  2340.8   521.3 2339.92
   555.6 2340.92   596.9 2343.27   638.9 2341.99   647.3 2340.77   655.7 2343.53
   664.2  2344.2   685.6 2342.97   722.7 2343.18   943.2 2344.04   976.5 2342.67
   982.3 2343.83   992.1 2350.53  1016.5 2370.23  1030.7 2379.53  1073.5 2403.25
    1103 2414.82  1123.2    2421  1159.1 2428.56  1179.6 2431.69  1212.9 2434.09
#Mann= 6 ,-1,0
       0     .05       0  438.21      .1       0   506.8    .045       0
   555.6     .08       0   722.7     .05       0   943.2      .1       0
#XS Ineff= 1 ,-1
  774.081194.614 2351.81
Permanent Ineff=
       F
Bank Sta=506.8,555.6
XS Rating Curve= 0 ,0
Exp/Cntr(USF)=0,0
Exp/Cntr=0.3,0.1

Type RM Length L Ch R = 1 ,12664   ,504.2,918.8,651.1
XS GIS Cut Line= 4
2259367.89940848419075.8931988142259923.66515207419093.296165009
2260718.21814855418787.053422661 2260807.0082123418663.836750934
#Sta/Elev= 30
       0 2353.77    20.3 2354.57   140.3 2348.67   216.4 2346.34   575.1  2343.2
   646.6 2340.53   714.3 2340.28   745.2 2341.18   754.6 2340.44   779.5 2340.13
   809.5 2341.24   841.2 2339.76   899.5 2340.87   921.6 2336.45   942.4 2335.66
     981 2336.95   998.1 2338.55  1053.9  2339.9  1079.6 2339.63  1094.9 2337.91
    1101 2336.69  1113.5 2336.61  1134.7 2338.05  1143.9 2337.54  1152.5 2340.86
  1345.4 2341.56  1444.4 2343.99  1479.1 2343.69  1538.1 2345.81  1559.4 2351.69
#Mann= 10 ,-1,0
       0     .05       0  636.04     .07       0   754.6      .1       0
  946.04     .08       0 1056.04      .1       0 1066.04     .08       0
  1094.9    .045       0  1134.7     .08       0  1152.5     .05       0
 1517.57      .1       0
#XS Ineff= 2 , 0
             723    2345 1235.15         2345.39
Permanent Ineff=
       F       F
Bank Sta=1094.9,1134.7
XS Rating Curve= 0 ,0
Exp/Cntr(USF)=0,0
Exp/Cntr=0.3,0.1

Type RM Length L Ch R = 1 ,11746   ,310.5,535.2,473.3
XS GIS Cut Line= 5
2259535.68015735419622.1317599862259981.22439533419474.109773259
2260117.70530399419486.1875013462260642.18520583419518.501936932
2261153.65234368419530.952461428
#Sta/Elev= 30
       0 2358.08    76.4  2353.4   129.9 2347.32   379.9 2342.19   437.8 2339.27
   447.3 2340.22     781 2337.75   837.4 2339.81   861.5  2335.6   885.5 2336.06
   897.5 2331.77   913.4 2331.95   921.6 2331.43   945.6 2332.25   955.2    2334
   965.7 2333.51   981.6 2336.62  1025.8 2336.68  1061.8 2334.61  1077.9 2337.84
  1093.9 2338.85    1154 2340.02  1442.1 2340.34  1542.8 2341.83  1554.1 2343.44
  1570.7 2351.78  1597.5 2351.38  1610.1 2349.44  1618.1 2352.21  1643.6 2354.65
#Mann= 7 ,-1,0
       0     .05       0   876.5      .1       0   913.4    .045       0
   945.6      .1       0 1171.98     .05       0  1570.7     .06       0
  1597.5      .1       0
#XS Ineff= 2 , 0
          610.48 2341.38 1122.34         2341.18
Permanent Ineff=
       F       F
Bank Sta=913.4,945.6
XS Rating Curve= 0 ,0
Exp/Cntr(USF)=0,0
Exp/Cntr=0.3,0.1

Type RM Length L Ch R = 1 ,11210   ,129.7,194,228.9
XS GIS Cut Line= 4
2259694.34893316419611.8178241772259894.94113298 419618.84676405
2260507.07885609419947.897264992 2261059.6796814419986.373246319
#Sta/Elev= 30
       0 2347.24   256.6 2340.53   279.3 2339.37   292.9  2336.8   333.3 2335.41
   362.8 2337.11   528.2 2337.24   602.7 2335.82   674.4 2337.09   896.8 2337.76
   912.9 2337.21   935.4 2332.02   960.9 2334.72     977 2334.53     993 2333.97
  1006.82331.388  1024.8 2330.94  1049.12331.371  1061.2 2335.16  1101.3 2332.98
  1117.3 2333.51  1133.4 2336.28  1181.5 2336.89  1289.7 2340.31  1301.8 2341.97
  1313.8 2346.81  1339.4 2346.39  1361.9 2344.94    1382 2349.36  1449.6 2355.89
#Mann= 7 ,-1,0
       0     .05       0     977      .1       0  1006.8    .045       0
  1049.1      .1       0  1181.5     .06       0  1313.8    .016       0
  1339.4     .06       0
Bank Sta=1006.8,1049.1
XS Rating Curve= 0 ,0
Exp/Cntr(USF)=0,0
Exp/Cntr=0.3,0.1

Type RM Length L Ch R = 1 ,11016   ,400.3,700.6,458.5
XS GIS Cut Line= 5
 2259646.2186719419861.0356968562259833.90170305419738.498841808
2260441.93267999420050.269827437 2260677.6997935420205.379770536
2261022.04386718420208.481969398
#Sta/Elev= 30
       0 2359.04   164.8 2350.34   235.7 2343.32   293.2 2340.45   330.1 2335.35
   788.6 2336.31     856 2335.58   905.5 2337.68   934.1 2336.68   962.8 2330.81
   972.4 2333.51   989.1 2333.27  1009.4 2330.66  1036.5 2330.13  1080.1 2330.61
  1093.1  2333.3  1136.4 2332.73  1154.3 2336.72  1168.2 2336.97  1326.7 2336.22
  1368.1    2339  1380.1 2341.87  1394.1 2343.04  1416.1 2342.01  1424.1 2342.68
  1440.1 2350.88  1460.1 2368.03  1464.1 2369.89  1491.1 2372.57    1534 2376.67
#Mann= 10 ,-1,0
       0     .05       0   788.6     .07       0   989.1      .1       0
  1009.4    .045       0  1080.1      .1       0  1168.2     .05       0
  1326.7     .07       0  1394.1    .016       0  1416.1     .08       0
  1491.1      .1       0
#XS Ineff= 2 , 0
                         1162.13          2343.9
Permanent Ineff=
       F       F
Bank Sta=1009.4,1080.1
XS Rating Curve= 0 ,0
Exp/Cntr(USF)=0,0
Exp/Cntr=0.3,0.1