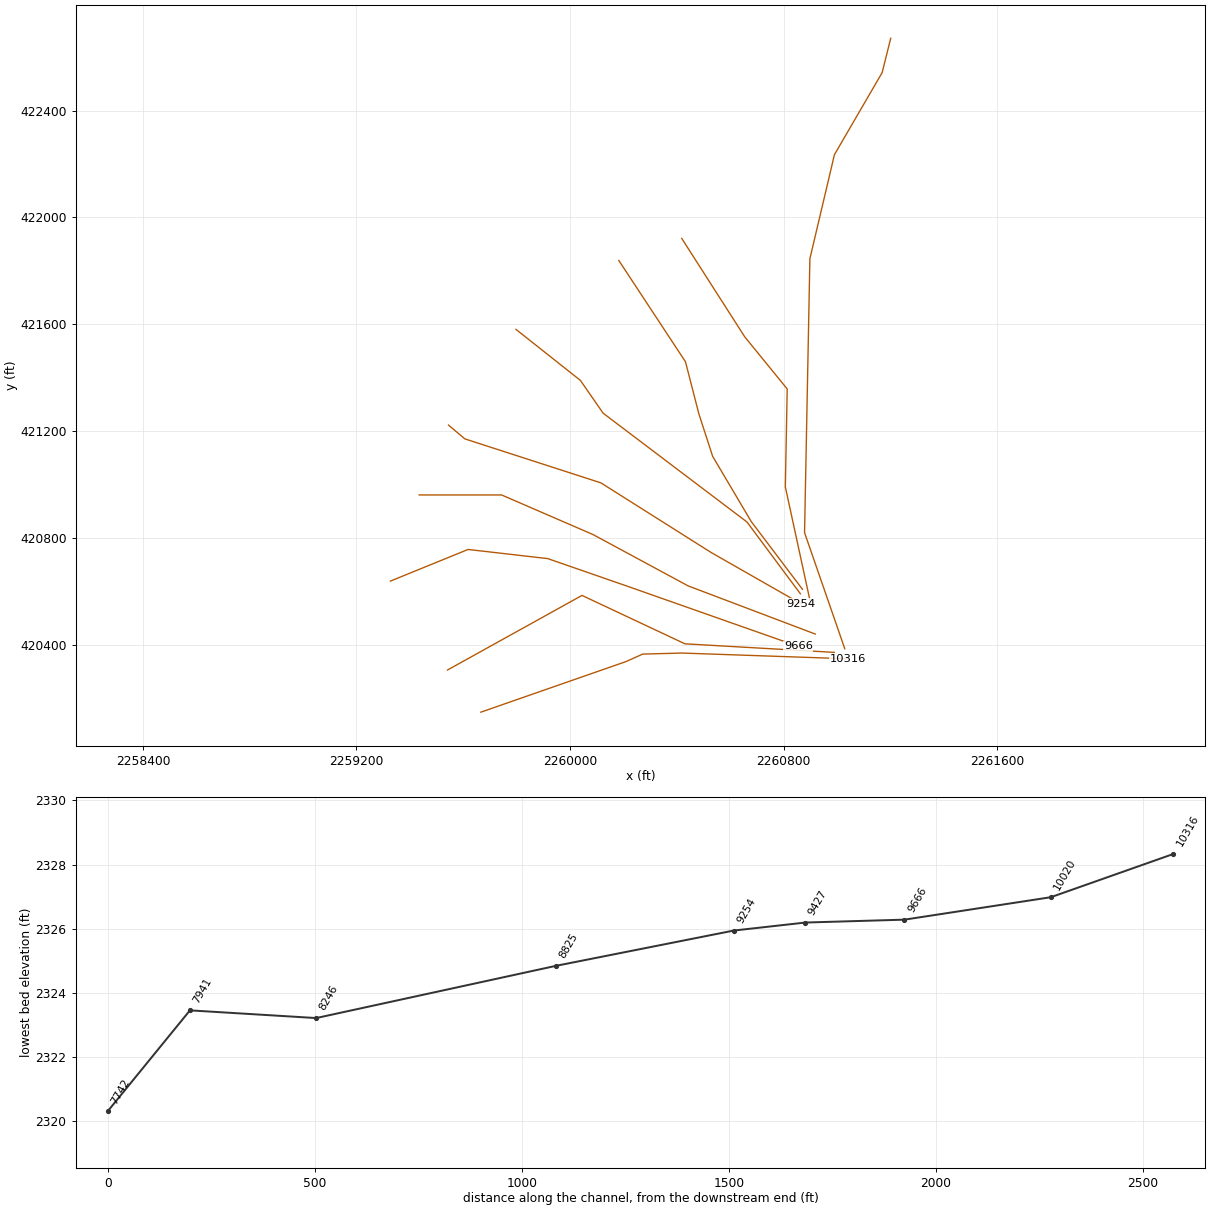
HEC-RAS study DOUTHTCK.prj: DOUTHTCK

--- DOUTHTCK.g01 (geometry) --- (continued)

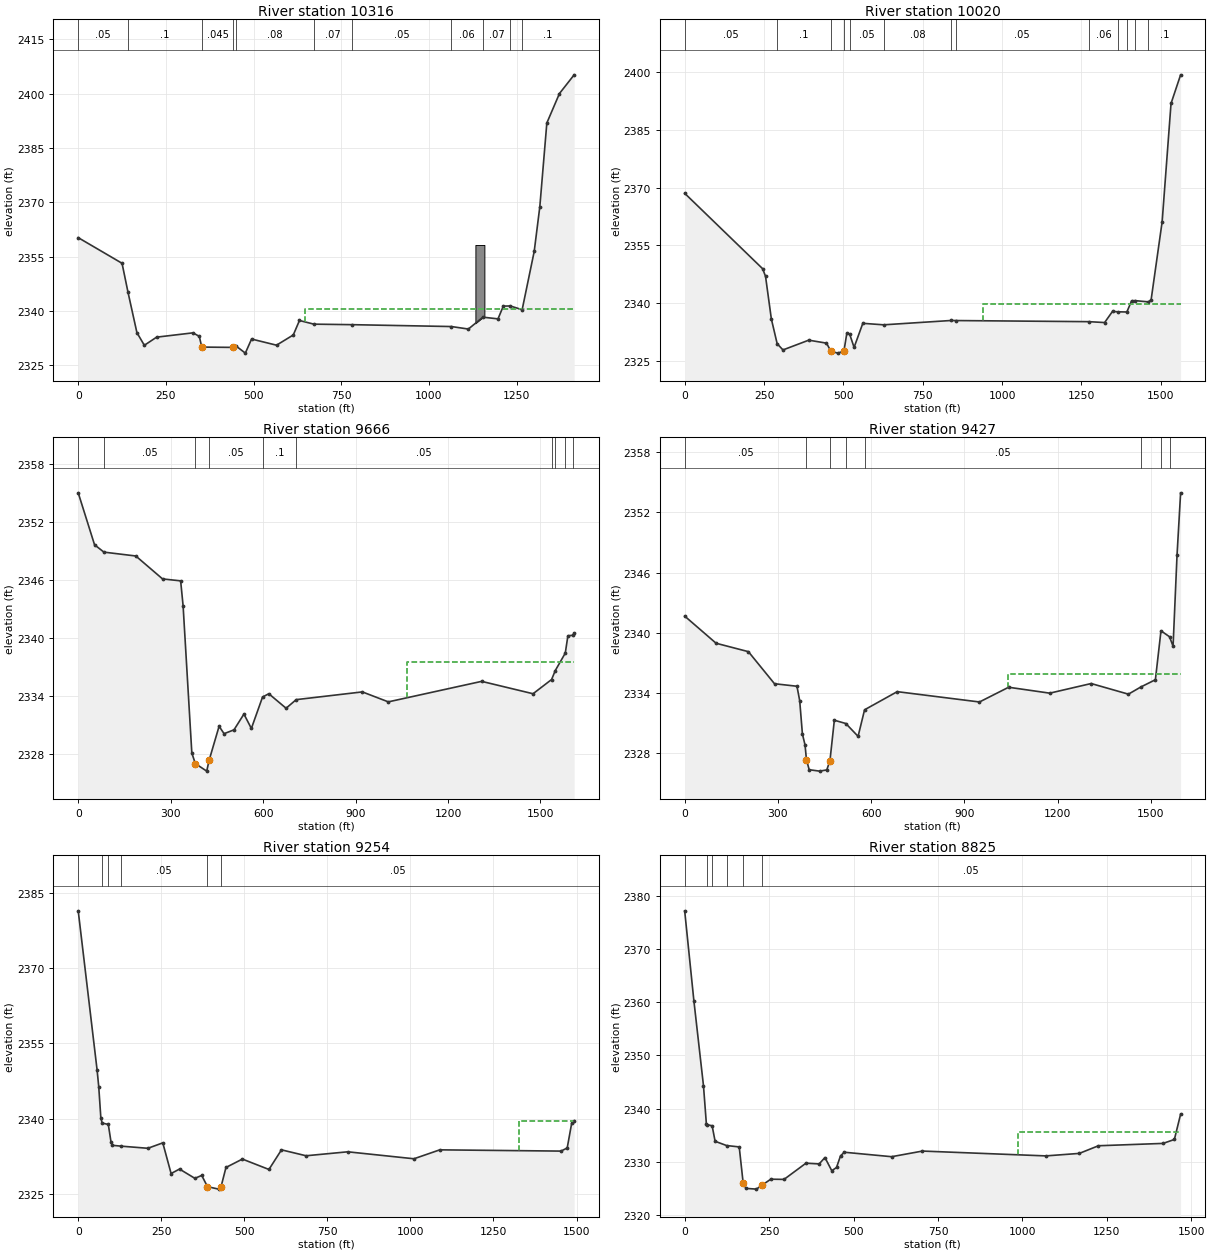
Type RM Length L Ch R = 1 ,10316   ,252.9,296.1,301.7
XS GIS Cut Line= 5
 2259666.1045143420146.4863818472260209.02995078420335.686423876
2260272.61459973420364.0800534692260419.66095623420367.970262927
2261042.02548911420346.406523487
#Sta/Elev= 30
       0 2360.22     125 2353.14     142 2345.14   167.4 2333.99   188.6 2330.49
   223.6 2332.74   327.3 2333.93   345.3 2332.96   352.4    2330   442.7 2329.91
   451.2 2330.22   476.6 2328.33   494.4 2332.22   565.6 2330.52   613.4 2333.35
     631 2337.34   672.2 2336.33   780.2 2336.19  1064.4 2335.67  1112.7 2334.98
  1154.2 2338.26  1197.2 2337.79  1212.4 2341.31    1232 2341.36  1266.1 2340.32
  1300.5 2356.43  1316.5 2368.77  1336.5 2391.88  1372.5 2400.02  1414.4 2405.18
#Mann= 11 ,-1,0
       0     .05       0     142      .1       0   352.4    .045       0
   442.7     .05       0   451.2     .08       0   672.2     .07       0
   780.2     .05       0  1064.4     .06       0  1154.2     .07       0
    1232    .016       0  1266.1      .1       0
#XS Ineff= 1 ,-1
  645.411411.014  2340.6
Permanent Ineff=
       F
#Block Obstruct= 1 ,-1
 1132.77 1158.41  2358.2
Bank Sta=352.4,442.7
XS Rating Curve= 0 ,0
Exp/Cntr(USF)=0,0
Exp/Cntr=0.3,0.1

Type RM Length L Ch R = 1 ,10020   ,337.9,353.4,121.8
XS GIS Cut Line= 4
2259541.33250629420304.5455279742260045.08229294 420583.89768239
2260430.67985691420402.5477591952260990.30007444 420370.49095459
#Sta/Elev= 30
       0 2368.54   245.7 2348.92   254.8 2346.93   273.1 2335.87   291.4 2329.43
   309.7 2327.81   390.9 2330.35   446.8 2329.58   460.6 2327.51   482.1 2326.98
   501.8  2327.5     511 2332.18   520.1 2331.86   533.8 2328.47   561.3 2334.73
   626.9 2334.34   840.2 2335.47   853.5 2335.45  1273.9 2335.16  1323.2 2334.93
  1348.2 2337.84  1364.9 2337.72  1393.3 2337.68  1408.3 2340.58  1420.3 2340.62
  1461.3 2340.31  1469.8 2340.87  1504.5 2361.14  1532.5 2391.89  1562.7 2399.34
#Mann= 13 ,-1,0
       0     .05       0   291.4      .1       0   460.6    .045       0
   501.8      .1       0   520.1     .05       0   626.9     .08       0
   840.2     .07       0   853.5     .05       0  1273.9     .06       0
  1364.9    .016       0  1393.3     .05       0  1420.3    .016       0
  1461.3      .1       0
#XS Ineff= 2 , 0
                          940.71         2339.63
Permanent Ineff=
       F       F
Bank Sta=460.6,501.8
XS Rating Curve= 0 ,0
Exp/Cntr(USF)=0,0
Exp/Cntr=0.3,0.1

Type RM Length L Ch R = 1 ,9666    ,239.7,239.1,148.8
XS GIS Cut Line= 5
2259327.09327122420637.4997637642259618.26883734420756.088518555
2259916.84096457420721.8060266232260209.06122724420620.433474467
2260855.36220163 420392.84022562
#Sta/Elev= 30
       0 2355.05      53 2349.68    83.4 2348.92   186.9 2348.52   273.7 2346.15
   332.4 2345.95   340.4 2343.37   368.7 2328.15   380.1 2327.06     417 2326.28
     425 2327.42   457.2 2330.92   473.3 2330.15   505.6 2330.55   537.8 2332.18
   561.9 2330.69   598.2 2333.94   618.5 2334.28   674.6 2332.78   707.4 2333.67
     922 2334.47  1006.3 2333.44  1309.2 2335.56    1476 2334.28  1536.2 2335.75
  1548.2 2336.68  1580.6 2338.48  1589.1 2340.27  1606.1 2340.33  1609.4 2340.55
#Mann= 10 ,-1,0
       0     .06       0    83.4     .05       0   380.1    .045       0
     425     .05       0   598.2      .1       0   707.4     .05       0
  1536.2     .07       0  1548.2    .016       0  1580.6     .05       0
  1606.1    .016       0
#XS Ineff= 2 , 0
                         1065.75         2337.55
Permanent Ineff=
       F       F
Bank Sta=380.1,425
XS Rating Curve= 0 ,0
Exp/Cntr(USF)=0,0
Exp/Cntr=0.3,0.1

Type RM Length L Ch R = 1 ,9427    ,166.5,172.9,187
XS GIS Cut Line= 5
2259435.08709674420960.3361593252259743.74832966420960.336159325
2260086.29818458420811.9589494382260442.58667005420619.618121807
2260918.85919561420439.184107315
#Sta/Elev= 30
       0 2341.66   101.1 2338.95   205.1 2338.11   289.1 2334.91   361.4 2334.66
   370.2 2333.22   378.9  2329.9   387.4  2328.8   391.9 2327.34   400.7 2326.33
   434.1 2326.19   457.4 2326.31   467.6 2327.24   481.7 2331.27   518.7 2330.94
   558.1 2329.66     579 2332.31   684.1 2334.12   948.8 2333.09  1042.6 2334.56
  1174.9 2333.97  1308.3 2334.93  1428.1 2333.87  1468.4 2334.59    1515 2335.31
    1533 2340.19  1560.5  2339.6  1571.9 2338.65  1584.7 2347.77  1596.2 2353.96
#Mann= 8 ,-1,0
       0     .05       0   391.9    .045       0   467.6     .05       0
   518.7      .1       0     579     .05       0  1468.4     .07       0
    1533    .016       0  1560.5      .1       0
#XS Ineff= 2 , 0
                         1039.11         2335.93
Permanent Ineff=
       F       F
Bank Sta=391.9,467.6
XS Rating Curve= 0 ,0
Exp/Cntr(USF)=0,0
Exp/Cntr=0.3,0.1

Type RM Length L Ch R = 1 ,9254    ,402,429.1,236.1
XS GIS Cut Line= 5
2259544.89702585421222.0083860752259606.32056332421170.356775023
 2260115.8567264421005.6300154522260529.06961481420744.579981217
2260866.34067509420552.045111046
#Sta/Elev= 30
       0 2381.41    56.9 2349.65    61.8 2346.34    68.2 2340.07    72.2 2339.11
    90.6 2338.83    98.5 2335.43   103.2 2334.67   128.4 2334.51   209.7 2334.08
   254.6 2335.16   279.6 2329.05     305 2329.94   351.2 2328.09   371.8 2328.67
   389.1 2326.43   422.6 2325.94     430 2326.43   444.8 2330.26   494.2 2331.93
   574.1 2329.86   611.9 2333.77   685.9 2332.59   811.3 2333.38  1010.7 2331.99
  1088.4 2333.77  1453.5 2333.52    1472 2334.15  1485.8 2339.19  1492.9 2339.56
#Mann= 6 ,-1,0
       0      .1       0    72.2    .016       0    90.6      .1       0
   128.4     .05       0   389.1    .045       0     430     .05       0
#XS Ineff= 2 , 0
                         1327.37         2339.46
Permanent Ineff=
       F       F
Bank Sta=389.1,430
XS Rating Curve= 0 ,0
Exp/Cntr(USF)=0,0
Exp/Cntr=0.3,0.1

Type RM Length L Ch R = 1 ,8825    ,542.8,579.2,261.3
XS GIS Cut Line= 5
2259797.57112316421580.7776844632260039.07730456421389.527124622
2260124.23266332421266.6800496882260663.08460565420859.051119224
2260863.21365863420590.016025117
#Sta/Elev= 30
       0 2377.19    27.2  2360.3    55.7 2344.28    64.2 2337.13    67.1 2336.96
    81.3 2336.75    90.1 2333.84     124 2333.04   161.5 2332.78   173.3 2325.92
   181.9 2324.98   212.5 2324.84   227.8 2325.53     255 2326.71   294.2 2326.67
   359.1 2329.72   398.2 2329.58   415.3 2330.78   435.6  2328.3   449.6 2328.91
   461.4 2331.09   472.5 2331.78   612.8 2330.94   704.1    2332  1069.6 2331.09
  1168.5 2331.56  1225.3    2333  1416.5 2333.44    1450 2334.18  1468.5 2338.94
#Mann= 6 ,-1,0
       0      .1       0    67.1    .016       0    81.3     .06       0
     124     .05       0   173.3    .045       0   227.8     .05       0
#XS Ineff= 2 , 0
                          987.94          2335.6
Permanent Ineff=
       F       F
Bank Sta=173.3,227.8
XS Rating Curve= 0 ,0
Exp/Cntr(USF)=0,0
Exp/Cntr=0.3,0.1

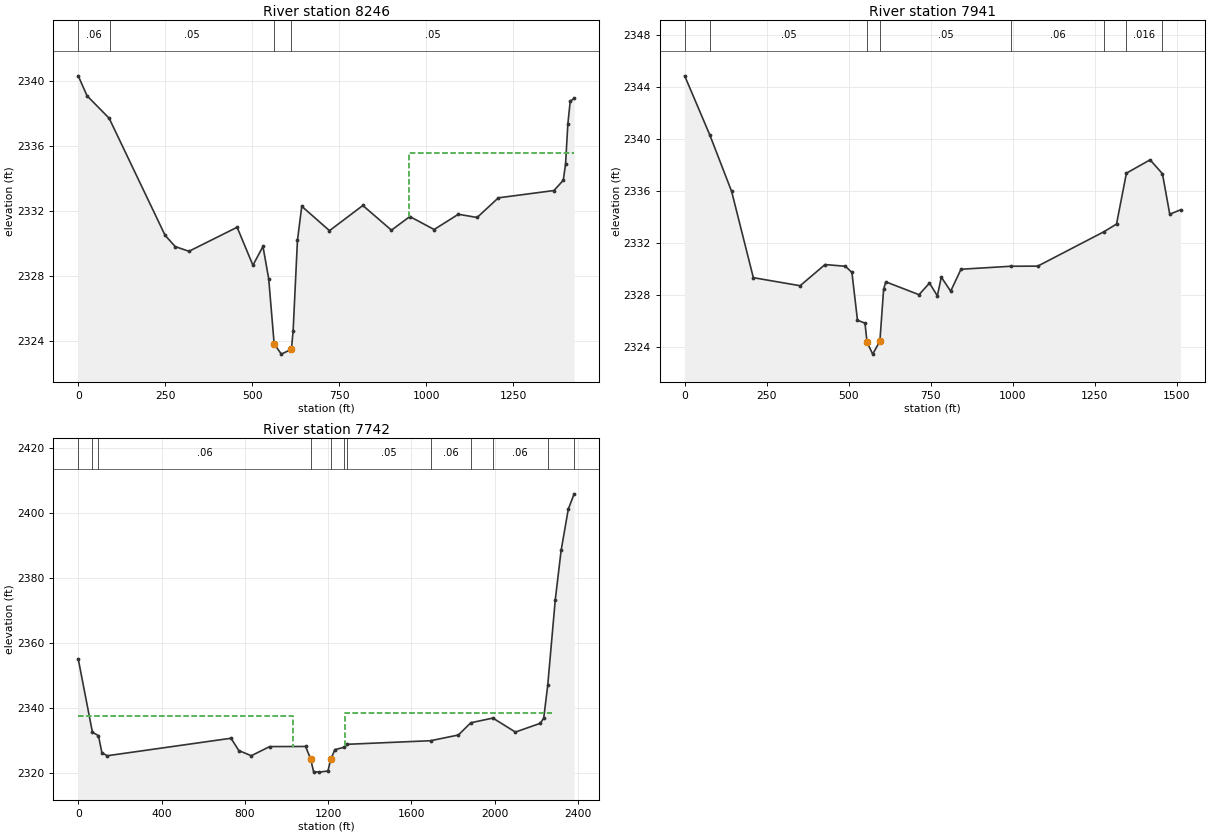
Type RM Length L Ch R = 1 ,8246    ,275.8,304.8,331.1
XS GIS Cut Line= 6
2260182.86422182421839.0357397232260432.74634015421459.326599016
2260483.00196171421263.8880707122260534.65357276421104.745269092
2260679.44066938420860.1496376892260871.05911955420606.753939077
#Sta/Elev= 30
       0 2340.34    25.4 2339.11    88.9 2337.73   249.8 2330.52   278.9 2329.83
   318.3 2329.54   456.8 2331.02   502.2 2328.68   531.1 2329.84   547.6 2327.84
   563.32323.832     584 2323.21   612.9 2323.51   617.8 2324.65   630.2 2330.21
   642.6 2332.31   722.3 2330.81   818.2 2332.36   900.4 2330.84   953.3 2331.68
  1023.1 2330.88  1092.8 2331.82  1146.7 2331.62  1207.6 2332.83  1367.5 2333.28
  1394.3 2333.91  1400.9 2334.91  1407.5 2337.38  1414.2 2338.76  1425.6 2338.96
#Mann= 4 ,-1,0
       0     .06       0      90     .05       0   563.3    .045       0
   612.9     .05       0
#XS Ineff= 2 , 0
                          950.08         2335.62
Permanent Ineff=
       F       F
Bank Sta=563.3,612.9
XS Rating Curve= 0 ,0
Exp/Cntr(USF)=0,0
Exp/Cntr=0.3,0.1

Type RM Length L Ch R = 1 ,7941    ,242.7,198.7,141.5
BEGIN DESCRIPTION:
structure xs 4
END DESCRIPTION:
XS GIS Cut Line= 5
2260418.78644527421921.3991195082260654.70866872421552.857894705
2260813.85147034  421357.4193664 2260806.8715229420990.274131085
2260903.19479757420546.349473936
#Sta/Elev= 30
       0 2344.89    76.8 2340.32   143.1 2335.98   209.2 2329.34   351.7 2328.72
   427.7 2330.35   489.6 2330.22   509.6 2329.74   526.5 2326.06   549.3 2325.84
   555.8 2324.36   572.9 2323.45   594.8 2324.45   606.1 2328.43   612.6 2329.02
   713.9 2328.03   745.9 2328.92   769.9 2327.94   781.9 2329.38   810.5  2328.3
   841.9 2329.99   993.8 2330.22  1075.7 2330.23  1277.5 2332.88  1315.8 2333.47
  1345.9 2337.39  1418.1 2338.42  1455.7 2337.35    1478 2334.23  1511.1 2334.57
#Mann= 8 ,-1,0
       0     .07       0    76.8     .05       0   555.8    .045       0
   594.8     .05       0   993.8     .06       0  1277.5     .05       0
  1345.9    .016       0  1455.7     .06       0
#Block Obstruct= 2 , 0
           21.89 2364.89
Bank Sta=555.8,594.8
XS Rating Curve= 0 ,0
Exp/Cntr(USF)=0,0
Exp/Cntr=0.5,0.3

Type RM Length L Ch R = 1 ,7742    ,135.5,124.6,139
BEGIN DESCRIPTION:
structure xs 3 - Channel burned from survey DOU042BU
END DESCRIPTION:
XS GIS Cut Line= 6
2261201.68286519 422671.369928382261169.65205418 422542.86630863
2260990.76106476422235.2219702242260898.84762499421845.286243033
2260878.84405649420819.0413656192261029.50156762420384.286833506
#Sta/Elev= 30
       0 2355.18    68.2 2332.58    97.1 2331.53   113.6 2326.31     139 2325.34
   733.6 2330.73   771.1 2326.94   830.8 2325.35   919.3 2328.16  1091.6  2328.2
  1115.7  2324.4 1129.96 2320.46 1156.52  2320.3 1199.03 2320.65  1212.1  2324.2
  1232.1 2327.21  1276.8 2327.96  1292.4 2328.87  1691.7 2329.97  1825.2 2331.73
  1884.8 2335.49  1990.8 2336.94    2099 2332.63  2218.4 2335.33  2234.9 2336.91
  2254.1 2347.01  2290.4 2373.37  2318.7 2388.64  2352.9 2401.26    2381 2405.96
#Mann= 12 ,-1,0
       0      .1       0    68.2     .06       0    97.1     .06       0
  1115.7    .045       0  1212.1     .08       0  1276.8     .06       0
  1292.4     .05       0  1691.7     .06       0  1884.8    .016       0
  1990.8     .06       0  2254.1      .1       0    2381      .1       0
#XS Ineff= 2 ,-1
       0    1030 2337.46    1282 2273.76 2338.64
Permanent Ineff=
       F       F
Bank Sta=1115.7,1212.1
XS Rating Curve= 0 ,0
Exp/Cntr(USF)=0,0
Exp/Cntr=0.5,0.3