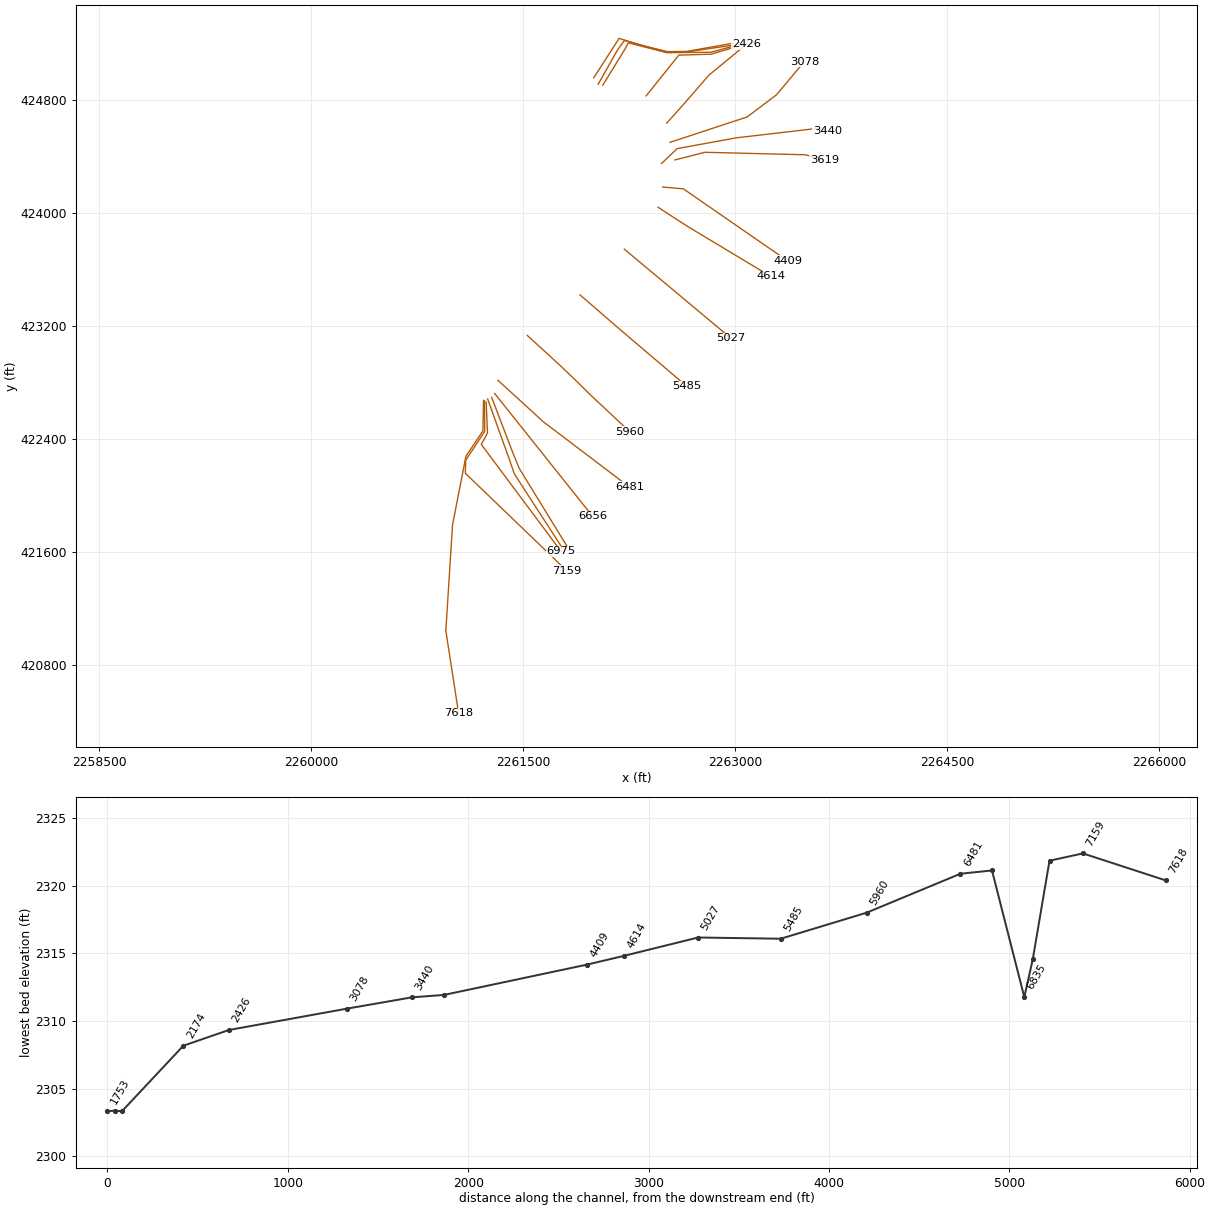
HEC-RAS study DOUTHTCK.prj: DOUTHTCK

--- DOUTHTCK.g01 (geometry) --- (continued)

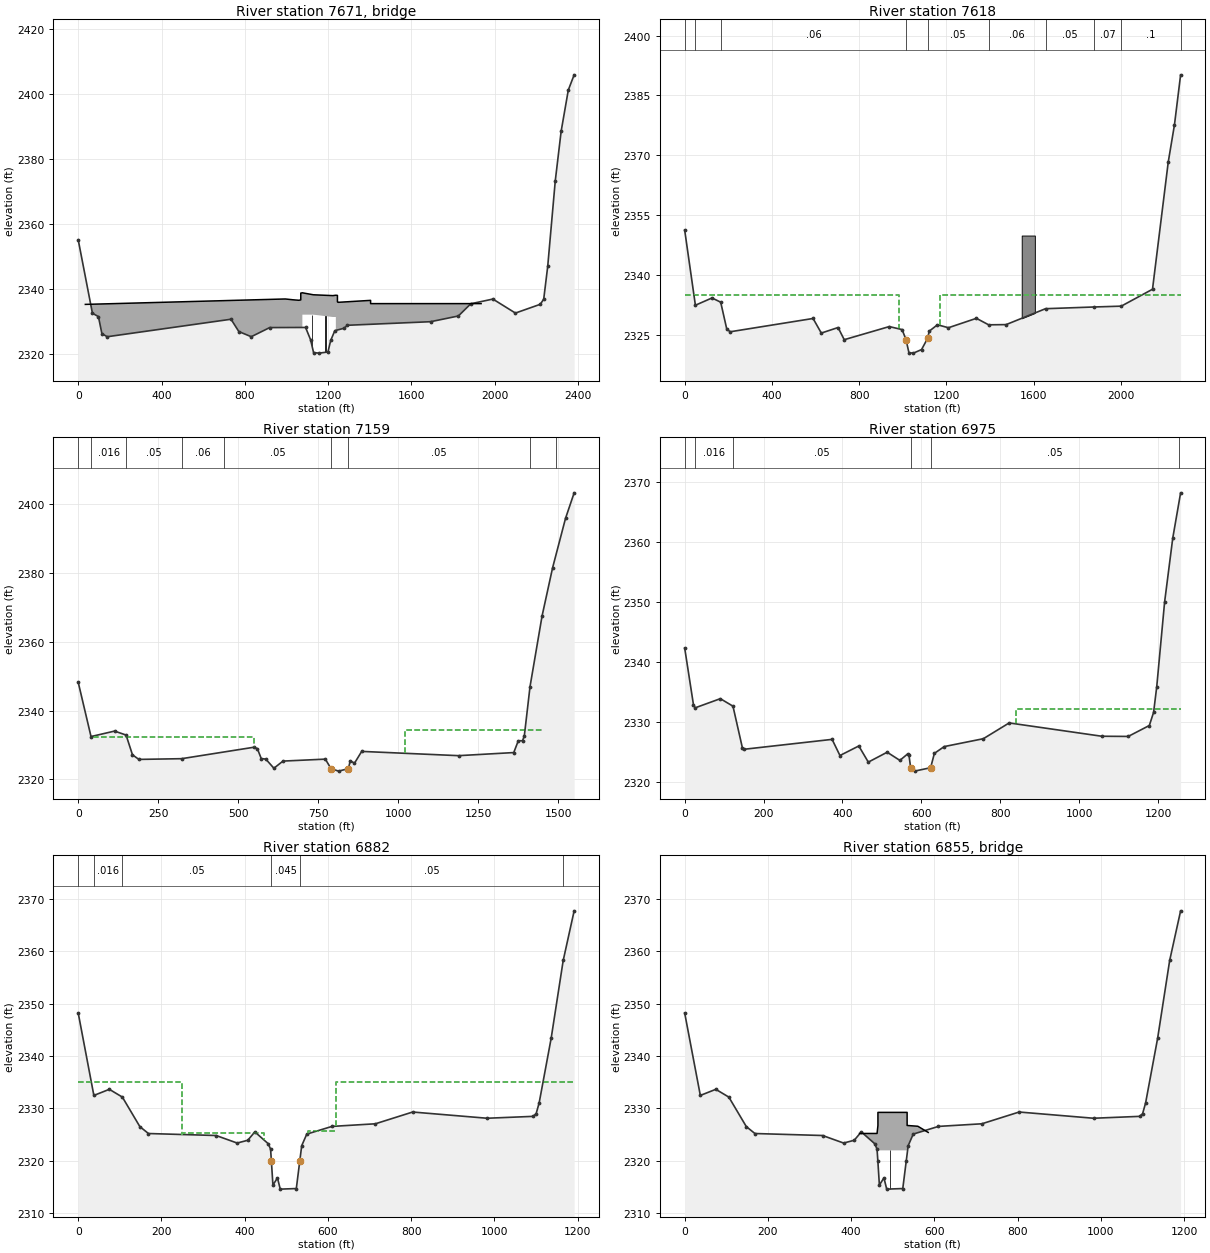
Type RM Length L Ch R = 3 ,7671    ,,,
BEGIN DESCRIPTION:
State Route 39
Survey ID: 54075DOU040
Included railing of 3.1 ft that spans approximately 180', covering the opening of the 160' structure
1' guardrail that spans the length length of the roadway, guardrail ends closer to bridge opening on the ROB f the DS face
END DESCRIPTION:
Bridge Culvert--1,0,-1,-1, 0
Deck Dist Width WeirC Skew NumUp NumDn MinLoCord MaxHiCord MaxSubmerge Is_Ogee
43.80016,28,2.6,0, 17, 16, , , 0.98, 0, 0,0,,
  34.265 994.2651027.8251058.9251068.5251068.5251076.1851128.8751222.7951236.855
1244.5251244.5251247.9251279.3151403.7451403.7451934.265
  2335.3 2336.97 2336.74 2336.572336.6812338.781 2338.87 2338.26    2338 2338.12
2338.0642336.064 2335.94 2336.06 2336.54 2335.54 2335.54
                                                 2332.14 2332.14 2331.42 2331.42
                                                        
       0     960 988.085 988.085  993.56  995.59 1094.61 1156.581164.0851164.085
 1213.66 1245.05 1284.14 1285.14    1900    2500
  2335.3 2336.972336.7772338.877 2338.84 2338.87 2338.26 2338.122338.109 2336.01
 2335.94 2336.062336.0892335.089 2335.54 2335.54
                                         2332.14 2332.14 2331.42
                                                
Pier Skew, UpSta & Num, DnSta & Num=  ,1123.125, 2 ,1044.16, 2 , 0 , 0 , 0 ,,
       3       3
       0    2345
       3       3
       0    2345
Pier Skew, UpSta & Num, DnSta & Num=  ,1188.31, 2 ,1109.53, 2 , 0 , 0 , 0 ,,
       3       3
       0    2345
       3       3
       0    2345
BR Coef=-1 ,-1 , 0 ,1.25, 0 ,,,0.8,0,2,0,
WSPro=,,,, 1 ,,,, 0 ,,,, 0 ,,,,-1 ,-1 ,-1 , 0 , 0 , 0 , 0 , 0
BR U #Sta/Elev= 30
       0 2355.18    68.2 2332.58    97.1 2331.53   113.6 2326.31     139 2325.34
   733.6 2330.73   771.1 2326.94   830.8 2325.35   919.3 2328.16  1091.6  2328.2
  1115.7  2324.4 1129.96 2320.46 1156.52  2320.3 1199.03 2320.65  1212.1  2324.2
  1232.1 2327.21  1276.8 2327.96  1292.4 2328.87  1691.7 2329.97  1825.2 2331.73
  1884.8 2335.49  1990.8 2336.94    2099 2332.63  2218.4 2335.33  2234.9 2336.91
  2254.1 2347.01  2290.4 2373.37  2318.7 2388.64  2352.9 2401.26    2381 2405.96
BR U #Mann= 12
       0      .1    68.2     .06    97.1     .06  1115.7     .04  1212.1     .08
  1276.8     .06  1292.4     .05  1691.7     .06  1884.8    .016  1990.8     .06
  2254.1      .1    2381      .1
BR D #Sta/Elev= 30
       0 2351.24    49.1  2332.4   125.1 2334.22   165.1 2333.17   193.1 2326.39
   209.1 2325.75   588.7 2329.08   626.4 2325.42   703.3 2326.81   731.5 2323.76
   938.1 2327.05   996.9 2326.29 1015.02 2323.72 1028.16 2320.49 1048.46 2320.39
 1085.99 2321.28 1114.42 2324.16  1121.1 2325.89    1159  2327.5  1209.3 2326.76
  1337.5 2329.12  1393.6 2327.49  1473.7 2327.54  1654.3 2331.53  1875.6 2331.96
  2001.6 2332.17  2144.9 2336.41  2217.1 2368.32  2245.6 2377.65  2273.8 2390.18
BR D #Mann= 10
       0     .07    49.1    .016   165.1     .06 1015.02     .04 1114.42     .05
  1393.6     .06  1654.3     .05  1875.6     .07  2001.6      .1  2273.8     .05
BC Design=,, 0 ,, 0 ,,,,,,
BC Use User HTab Curves=0
BC User HTab FreeFlow(D)= 0

Type RM Length L Ch R = 1 ,7618    ,381.5,458.3,519.4
BEGIN DESCRIPTION:
structure xs 2 - Channel burned from survey DOU038BD
END DESCRIPTION:
XS GIS Cut Line= 6
2261218.89958161422674.2810026552261214.59508129422459.055986758
2261094.06907239422278.2669734042260999.37006539421791.858437475
 2260952.0205619421042.8753821522261042.41506857420457.463338911
#Sta/Elev= 30
       0 2351.24    49.1  2332.4   125.1 2334.22   165.1 2333.17   193.1 2326.39
   209.1 2325.75   588.7 2329.08   626.4 2325.42   703.3 2326.81   731.5 2323.76
   938.1 2327.05   996.9 2326.29 1015.02 2323.72 1028.16 2320.49 1048.46 2320.39
 1085.99 2321.28 1114.42 2324.16  1121.1 2325.89    1159  2327.5  1209.3 2326.76
  1337.5 2329.12  1393.6 2327.49  1473.7 2327.54  1654.3 2331.53  1875.6 2331.96
  2001.6 2332.17  2144.9 2336.41  2217.1 2368.32  2245.6 2377.65  2273.8 2390.18
#Mann= 10 ,-1,0
       0     .07       0    49.1    .016       0   165.1     .06       0
 1015.02    .045       0 1114.42     .05       0  1393.6     .06       0
  1654.3     .05       0  1875.6     .07       0  2001.6      .1       0
  2273.8     .05       0
#XS Ineff= 2 ,-1
       0     982    2335    1169 2273.76    2335
Permanent Ineff=
       F       F
#Block Obstruct= 1 ,-1
 1545.24 1605.45 2349.88
Bank Sta=1015.02,1114.42
XS Rating Curve= 0 ,0
Exp/Cntr(USF)=0,0
Exp/Cntr=0.5,0.3

Type RM Length L Ch R = 1 ,7159    ,200.1,185,177.8
BEGIN DESCRIPTION:
structue xs 1
END DESCRIPTION:
XS GIS Cut Line= 5
2261225.44402173 422670.780913692261227.23425328422455.528604805
2261092.55587044422249.5333286942261089.73506636422158.331793858
2261808.44326038421466.502423648
#Sta/Elev= 30
       0 2348.24      40 2332.44   113.6 2334.03   149.6 2332.88   169.6 2327.13
   189.6 2325.79   323.2    2326   549.8 2329.34     560 2328.92   572.1 2326.04
   586.3 2325.88   611.7 2323.22     640  2325.3   772.5 2325.87   790.22323.111
   813.8 2322.38   844.7 2323.11   850.3 2325.41   863.5 2324.68   886.1 2328.12
  1188.9 2326.88  1361.4 2327.78  1375.6 2331.21  1388.8 2331.23  1394.4  2332.6
  1412.3 2346.99  1449.9 2367.52  1482.9 2381.58  1523.3 2395.95  1550.2 2403.36
#Mann= 9 ,-1,0
       0      .1       0      40    .016       0   149.6     .05       0
  325.26     .06       0  455.26     .05       0   790.2    .045       0
   844.7     .05       0 1412.62      .1       0 1492.62     .12       0
#XS Ineff= 2 ,-1
   47.77  548.062332.232 1022.841453.2332334.432
Permanent Ineff=
       F       F
Bank Sta=790.2,844.7
XS Rating Curve= 0 ,0
Exp/Cntr(USF)=0,0
Exp/Cntr=0.3,0.1

Type RM Length L Ch R = 1 ,6975    ,118,92.8,75.5
BEGIN DESCRIPTION:
structure xs 4
END DESCRIPTION:
XS GIS Cut Line= 4
2261237.22365007422663.5057442782261246.86816872422443.907473645
 2261203.0968918422362.3000082082261767.51952521421604.656792265
#Sta/Elev= 30
       0 2342.35    22.3 2332.89    26.4 2332.38    90.4 2333.91   122.4 2332.66
   146.5 2325.66   150.5 2325.48   373.7 2327.13   393.6 2324.44   441.4 2326.03
   465.5 2323.34   513.3 2324.99   545.5 2323.63   565.5 2324.72   568.4 2324.59
  572.83  2322.4   582.7 2321.84  623.48 2322.41     633  2324.8     658 2325.93
   757.1 2327.24   822.6 2329.87  1057.4 2327.65  1124.4 2327.62  1177.9 2329.44
  1188.7 2331.63  1196.7 2335.92  1216.6    2350  1237.3 2360.67  1257.2  2368.2
#Mann= 6 ,-1,0
       0      .1       0    26.4    .016       0   122.4     .05       0
  572.83    .045       0  623.48     .05       0 1252.42      .1       0
#XS Ineff= 2 , 0
                          839.21         2332.19
Permanent Ineff=
       F       F
Bank Sta=572.83,623.48
XS Rating Curve= 0 ,0
Exp/Cntr(USF)=0,0
Exp/Cntr=0.5,0.3

Type RM Length L Ch R = 1 ,6882    ,45.4,47,66.5
BEGIN DESCRIPTION:
structure xs 3 - Channel burned based on survey:54075DOU032BU
END DESCRIPTION:
XS GIS Cut Line= 4
2261247.92687828422684.6139431072261398.01552391422265.866621807
2261437.03857177422153.3001375872261777.73979735421626.488991435
#Sta/Elev= 30
       0 2348.23    37.6 2332.47    74.8 2333.64   106.1 2332.15   148.1 2326.51
   168.7 2325.19   331.3 2324.81   381.8 2323.37   407.3  2323.9   424.3  2325.5
   456.5 2323.24  462.13  2322.2  464.02 2319.99  467.75 2315.33  478.67 2316.71
  485.34 2314.56  523.95 2314.67  532.29 2319.95   536.9 2322.86   549.1 2325.08
   609.7 2326.55   713.9 2327.05   803.5  2329.3   982.2 2328.11  1092.9 2328.47
  1100.1 2328.99  1107.3 2331.04  1136.2 2343.41  1165.1 2358.27  1191.4 2367.76
#Mann= 6 ,-1,0
       0      .1       0    37.6    .016       0   106.1     .05       0
  464.02    .045       0  532.29     .05       0  1165.1      .1       0
#XS Ineff= 4 ,-1
       0     250    2335     250     446 2325.26     552     620 2325.67
     6201191.352    2335
Permanent Ineff=
       F       F       F       F
Bank Sta=464.02,532.29
XS Rating Curve= 0 ,0
Exp/Cntr(USF)=0,0
Exp/Cntr=0.5,0.3

Type RM Length L Ch R = 3 ,6855    ,,,
BEGIN DESCRIPTION:
Unnamed Road
Survey ID: 54075DOU030
Top of road is collapsing, added 2.5 ft railing
structure is failing but modeled consistent rail height and low chord
END DESCRIPTION:
Bridge Culvert--1,0,-1,-1, 0
Deck Dist Width WeirC Skew NumUp NumDn MinLoCord MaxHiCord MaxSubmerge Is_Ogee
16.03504,15,2.6,0, 8, 7, , , 0.98, 0, 0,0,,
     420  462.13  464.25  464.25  534.38  534.38  560.09     585
  2325.2  2325.2 2326.73 2329.23 2329.23 2326.73 2326.58  2325.4
                 2321.97 2321.97 2321.97 2321.97
     440     450  455.25  455.25  512.91  512.91   534.1
  2325.2  2325.2 2326.73 2329.23 2329.23 2326.73  2325.4
                 2321.97 2321.97 2321.97 2321.97
Pier Skew, UpSta & Num, DnSta & Num=  ,493.5, 2 ,484.49, 2 , 0 , 0 , 0 ,,
     1.5     1.5
       0    2330
     1.5     1.5
       0    2330
BR Coef=-1 ,-1 , 0 ,1.25, 0 ,,,0.8,0,2,0,
WSPro=,,,, 1 ,,,, 0 ,,,, 0 ,,,,-1 ,-1 ,-1 , 0 , 0 , 0 , 0 , 0
BR U #Sta/Elev= 30
       0 2348.23    37.6 2332.47    74.8 2333.64   106.1 2332.15   148.1 2326.51
   168.7 2325.19   331.3 2324.81   381.8 2323.37   407.3  2323.9   424.3  2325.5
   456.5 2323.24  462.13  2322.2  464.02 2319.99  467.75 2315.33  478.67 2316.71
  485.34 2314.56  523.95 2314.67  532.29 2319.95   536.9 2322.86   549.1 2325.08
   609.7 2326.55   713.9 2327.05   803.5  2329.3   982.2 2328.11  1092.9 2328.47
  1100.1 2328.99  1107.3 2331.04  1136.2 2343.41  1165.1 2358.27  1191.4 2367.76
BR U #Mann= 6
       0      .1    37.6    .016   106.1     .05  464.02     .04  532.29     .05
  1165.1      .1
BR D #Sta/Elev= 30
       0 2346.77   26.08 2333.75   32.28  2331.7   49.18 2333.25   84.95 2332.31
   96.28 2331.11  115.93  2325.3  345.21  2323.2  435.92 2325.43   453.5 2321.82
  466.07 2316.86  467.25 2315.99  467.29 2311.77   470.9 2316.35  475.25 2317.22
  516.27 2321.01  529.78 2325.35  563.49 2324.84  603.17 2328.42  650.96 2327.43
  699.16 2330.25  763.56 2331.06  777.64 2329.12  791.72 2331.01   801.1 2329.85
  876.17 2331.33 1053.29 2328.23 1077.28 2334.07 1134.22  2357.3 1185.46 2372.62
BR D #Mann= 5
       0      .1   26.08    .016   32.28     .05   453.5     .04  516.27     .05
BC Design=,, 0 ,, 0 ,,,,,,
BC Use User HTab Curves=0
BC User HTab FreeFlow(D)= 0

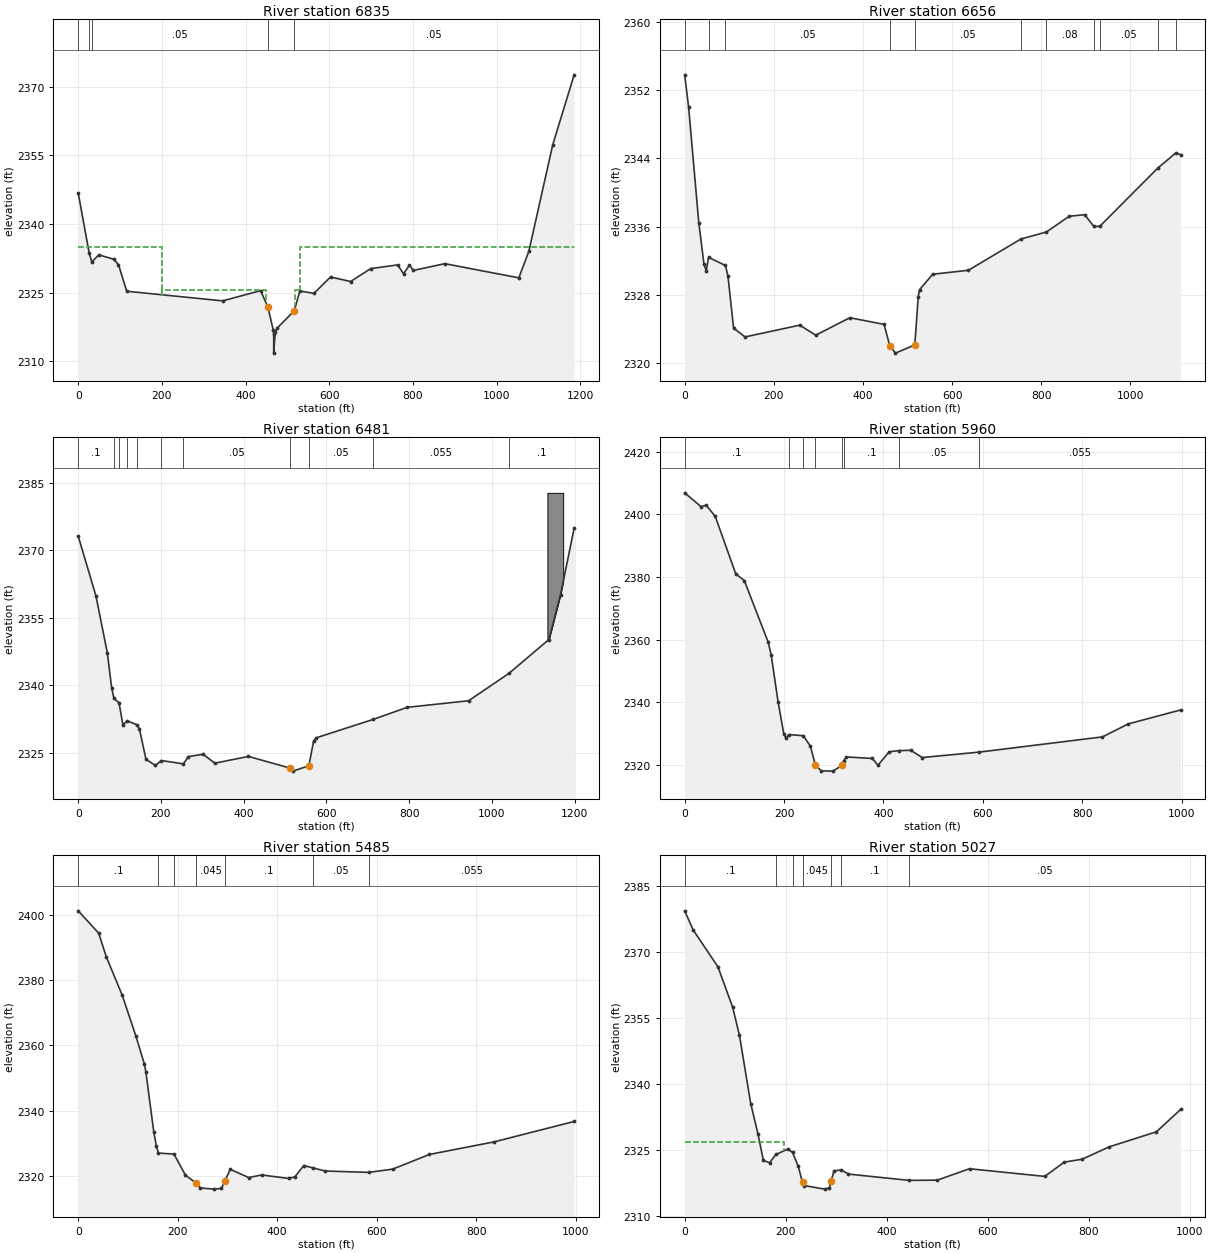
Type RM Length L Ch R = 1 ,6835    ,157.3,179,203.9
BEGIN DESCRIPTION:
structure xs 2 - Channel burned based on survey 54075DOU028BD
END DESCRIPTION:
XS GIS Cut Line= 4
2261276.44372095422695.1201483012261429.53413949422294.383464477
2261471.55896027 422192.323185452261809.25841293421641.497855998
#Sta/Elev= 30
       0 2346.77   26.08 2333.75   32.28  2331.7   49.18 2333.25   84.95 2332.31
   96.28 2331.11  115.93  2325.3  345.21  2323.2  435.92 2325.43   453.5 2321.82
  466.07 2316.86  467.25 2315.99  467.29 2311.77   470.9 2316.35  475.25 2317.22
  516.27 2321.01  529.78 2325.35  563.49 2324.84  603.17 2328.42  650.96 2327.43
  699.16 2330.25  763.56 2331.06  777.64 2329.12  791.72 2331.01   801.1 2329.85
  876.17 2331.33 1053.29 2328.23 1077.28 2334.07 1134.22  2357.3 1185.46 2372.62
#Mann= 5 ,-1,0
       0      .1       0   26.08    .016       0   32.28     .05       0
   453.5    .045       0  516.27     .05       0
#XS Ineff= 4 ,-1
       0     200    2335     200     450  2325.5     518     530  2325.5
     530 1185.46    2335
Permanent Ineff=
       F       F       F       F
Bank Sta=453.5,516.27
XS Rating Curve= 0 ,0
Exp/Cntr(USF)=0,0
Exp/Cntr=0.5,0.3

Type RM Length L Ch R = 1 ,6656    ,147.1,174.6,180.5
BEGIN DESCRIPTION:
structure xs 1
END DESCRIPTION:
XS GIS Cut Line= 2
2261297.53639762422722.9994820092261990.87784327421852.832701223
#Sta/Elev= 30
       0 2353.83     8.9    2350    31.6 2336.47    43.2  2331.6    48.4 2330.77
    53.5 2332.38    91.4 2331.42    97.1 2330.18   109.7 2324.07   135.3 2323.02
   258.1 2324.41   293.9 2323.23   370.6 2325.28   447.3  2324.5     460    2322
   472.9 2321.12   516.32322.086     524 2327.76   526.9 2328.57   556.3 2330.39
   636.5 2330.86   754.2 2334.53   811.6 2335.36   862.8 2337.21   897.4 2337.39
   917.8 2336.02   931.1 2336.02    1061 2342.85  1102.3 2344.67  1112.6 2344.45
#Mann= 11 ,-1,0
       0      .1       0    53.5    .016       0    91.4     .05       0
     460    .045       0   516.3     .05       0   754.2    .055       0
   811.6     .08       0   917.8    .045       0   931.1     .05       0
    1061      .1       0  1102.3     .05       0
Bank Sta=460,516.3
XS Rating Curve= 0 ,0
Exp/Cntr(USF)=0,0
Exp/Cntr=0.3,0.1

Type RM Length L Ch R = 1 ,6481    ,392.9,520.8,368.5
XS GIS Cut Line= 4
2261320.50248641422816.9490738192261644.37311586422520.596863859
2261773.49800734422423.2239948722262249.77834478422061.250938421
#Sta/Elev= 30
       0  2373.2    42.9 2359.87    70.4 2347.19    80.9 2339.38    86.3 2337.08
    98.7 2336.08     108 2331.18   118.2 2332.09   141.9  2331.2   147.8 2330.35
   163.8 2323.52   186.5 2322.15   201.1 2323.24   254.4  2322.5   266.3 2324.11
   301.9 2324.63   330.3 2322.65   411.6 2324.15   511.1 2321.58   518.9 2320.88
   557.6 2322.07     569 2327.55   575.5  2328.3   712.6 2332.38   795.3 2335.08
   943.8 2336.55  1041.2 2342.63  1137.9 2350.18    1166 2360.17 1198.94 2374.96
#Mann= 11 ,-1,0
       0      .1       0    86.3     .06       0    98.7      .1       0
   118.2    .016       0   141.9     .05       0   201.1    .025       0
   254.4     .05       0   511.1    .045       0   557.6     .05       0
   712.6    .055       0  1041.2      .1       0
#Block Obstruct= 1 ,-1
 1134.28 1172.43 2382.84
Bank Sta=511.1,557.6
XS Rating Curve= 0 ,0
Exp/Cntr(USF)=0,0
Exp/Cntr=0.3,0.1

Type RM Length L Ch R = 1 ,5960    ,473.2,475.5,488
XS GIS Cut Line= 5
2261528.20223943423134.7250960862261764.47699194422918.241000058
2261873.22941145422813.8874212922261979.78305284422708.811828347
2262254.87614656422450.850281121
#Sta/Elev= 30
       0 2406.84    32.5 2402.47    43.5 2402.87    61.5 2399.32   102.9 2380.93
     120 2378.83   168.1 2359.14     174 2355.16   187.9 2340.15   199.3 2330.01
   203.6 2328.48   209.5 2329.67   238.7 2329.31     253 2325.97   262.8 2320.04
   274.7 2318.09   298.3    2318   316.1 2319.81     320 2321.38   325.6 2322.53
   377.6 2322.05   388.9 2319.87   411.5 2324.18   430.9 2324.55   454.9 2324.64
   477.9 2322.34   591.8 2324.06   840.7 2328.93   892.5 2333.07   997.9 2337.53
#Mann= 8 ,-1,0
       0      .1       0   209.5    .016       0   238.7      .1       0
   262.8    .045       0   316.1     .06       0     320      .1       0
   430.9     .05       0   591.8    .055       0
Bank Sta=262.8,316.1
XS Rating Curve= 0 ,0
Exp/Cntr(USF)=0,0
Exp/Cntr=0.3,0.1

Type RM Length L Ch R = 1 ,5485    ,454.9,457.9,462.3
XS GIS Cut Line= 4
2261900.98770608423421.6361711732262009.90368954423328.078531225
 2262144.4170112 423210.828672892262658.21444601422772.956786363
#Sta/Elev= 30
       0 2401.13    41.1 2394.31    56.5 2387.05    88.6 2375.31     116 2362.84
   133.1 2354.27     136 2351.93   151.9 2333.61   157.2 2329.16   161.4 2327.11
   192.6 2326.78   215.6 2320.33   236.8 2317.97   245.4 2316.43   273.9 2316.08
     288 2316.31   295.2  2318.7   305.8 2322.14   342.7 2319.62     369 2320.41
   423.2 2319.34   435.6 2319.84   453.5 2323.28   472.6 2322.55   496.1 2321.62
   584.1  2321.2   632.3 2322.19   706.1 2326.68   836.4 2330.53   997.1 2336.76
#Mann= 7 ,-1,0
       0      .1       0   161.4    .016       0   192.6      .1       0
   236.8    .045       0   295.2      .1       0   472.6     .05       0
   584.1    .055       0
Bank Sta=236.8,295.2
XS Rating Curve= 0 ,0
Exp/Cntr(USF)=0,0
Exp/Cntr=0.3,0.1

Type RM Length L Ch R = 1 ,5027    ,408.1,412.6,467.9
XS GIS Cut Line= 3
2262215.26340574423745.0701355862262540.60035309423473.258793135
2262968.83874566423114.807704879
#Sta/Elev= 30
       0 2379.38    16.8 2375.04    65.9 2366.66      95 2357.49   108.5  2351.1
   130.8 2335.61   145.4 2328.59   155.8 2322.69   168.3 2322.17   180.8 2324.04
   204.5 2325.28   213.6 2324.51   224.9 2321.37   233.4 2317.69   236.3 2316.99
   277.4 2316.17   286.8 2316.47   290.2 2318.04   295.9 2320.32   310.1 2320.54
   324.3 2319.59   444.3 2318.16   500.4 2318.21   564.2  2320.8   713.3 2319.06
     752 2322.31   787.2 2322.96   841.1 2325.78   934.6  2329.2   982.4 2334.27
#Mann= 7 ,-1,0
       0      .1       0   180.8    .016       0   213.6      .1       0
   233.4    .045       0   290.2     .06       0   310.1      .1       0
   444.3     .05       0
#XS Ineff= 2 , 0
          197.18 2326.88
Permanent Ineff=
       F       F
Bank Sta=233.4,290.2
XS Rating Curve= 0 ,0
Exp/Cntr(USF)=0,0
Exp/Cntr=0.3,0.1

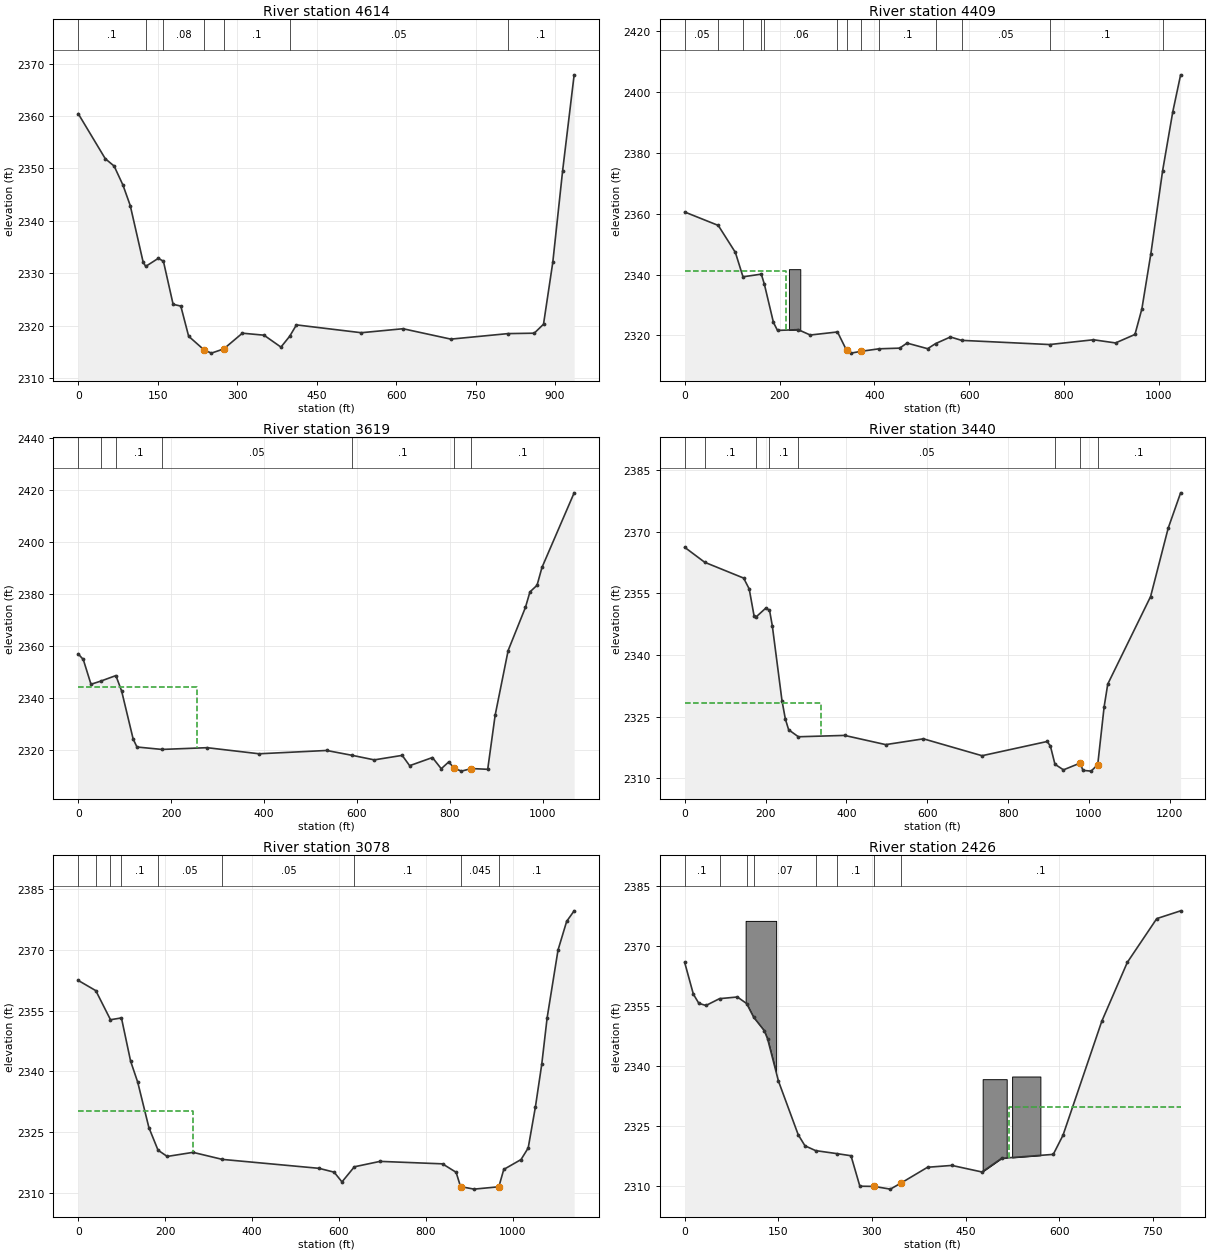
Type RM Length L Ch R = 1 ,4614    ,204,205.8,183.4
XS GIS Cut Line= 4
2262453.66804876424042.644441673  2262499.708641424011.929145093
2262661.29411853423907.2150121792263250.79879699423552.447089789
#Sta/Elev= 30
       0 2360.45    51.1 2351.86    67.8 2350.46    84.5 2346.82    98.2 2342.93
   122.6 2332.13   127.4 2331.34   151.2 2332.88   160.8 2332.32   179.1 2324.11
   193.6 2323.78   208.4 2318.03     237 2315.47     237 2315.46   251.3 2314.81
   274.6 2315.61   309.8 2318.61   350.6 2318.23   382.6 2315.96   399.2 2318.04
   411.8 2320.19   534.2  2318.7   612.9 2319.46   703.2 2317.48   811.1 2318.53
   860.6 2318.61   878.1 2320.32   895.6 2332.11   914.2  2349.6935.9177 2367.85
#Mann= 7 ,-1,0
       0      .1       0   127.4    .016       0   160.8     .08       0
     237    .045       0   274.6      .1       0   399.2     .05       0
   811.1      .1       0
Bank Sta=237,274.6
XS Rating Curve= 0 ,0
Exp/Cntr(USF)=0,0
Exp/Cntr=0.3,0.1

Type RM Length L Ch R = 1 ,4409    ,511.3,790,685
XS GIS Cut Line= 3
2262485.63382787424185.3879501692262632.63152095424172.824044778
2263371.38915794423661.473095364
#Sta/Elev= 30
       0 2360.54    70.8 2356.13   106.9 2347.26     123 2339.24   161.6 2340.12
     168 2336.85   187.2 2324.25   195.8 2321.62   239.4 2321.88   264.8 2320.11
   322.3 2321.12   341.6 2315.04   350.7 2314.16   372.82314.771   409.7 2315.58
   453.5  2315.8   468.9 2317.46   512.4 2315.62   529.3  2317.3   560.5 2319.47
   583.9 2318.36   769.7 2316.98   862.1 2318.55   908.8 2317.51   949.7  2320.3
   964.3 2328.71   983.3 2346.89    1008 2374.08  1029.5 2393.49    1046 2405.62
#Mann= 13 ,-1,0
       0     .05       0    70.8      .1       0     123    .016       0
   161.6     .07       0     168     .06       0   322.3      .1       0
   341.6    .045       0   372.8     .05       0   409.7      .1       0
   529.3     .08       0   583.9     .05       0   769.7      .1       0
    1008     .12       0
#XS Ineff= 2 , 0
          212.74 2341.27
Permanent Ineff=
       F       F
#Block Obstruct= 1 ,-1
  219.89  243.82 2341.75
Bank Sta=341.6,372.8
XS Rating Curve= 0 ,0
Exp/Cntr(USF)=0,0
Exp/Cntr=0.3,0.1

Type RM Length L Ch R = 1 ,3619    ,135.9,178.3,172.3
XS GIS Cut Line= 4
2262573.58116561424377.6157026522262784.65477618424431.640495833
2263497.02821185424414.0510282862263628.94921845424376.359312113
#Sta/Elev= 30
       0 2356.94    10.9 2354.79    27.5 2345.28    48.1 2346.46    81.1 2348.61
    93.5 2342.66   118.3 2324.24   126.5 2321.19   180.2 2320.26   277.4 2320.93
   389.5 2318.59   534.9 2319.86   589.5    2318   637.4 2316.25   697.5 2317.98
   713.5 2314.02   762.6 2317.15   781.6 2312.85   797.7 2315.47   809.4 2313.04
   825.1 2311.93   846.6 2312.92   881.6 2312.63   897.6 2333.38   925.6 2358.24
   962.8 2374.78   972.5 2380.73   987.8 2383.29   998.4 2390.12  1067.7 2418.78
#Mann= 7 ,-1,0
       0      .1       0    48.1    .016       0    81.1      .1       0
   180.2     .05       0   589.5      .1       0   809.4    .045       0
   846.6      .1       0
#XS Ineff= 2 , 0
          256.11  2344.2
Permanent Ineff=
       F       F
Bank Sta=809.4,846.6
XS Rating Curve= 0 ,0
Exp/Cntr(USF)=0,0
Exp/Cntr=0.3,0.1

Type RM Length L Ch R = 1 ,3440    ,163.7,362.2,392.5
XS GIS Cut Line= 5
2262478.77040955424352.4262802722262588.53919561 424457.40365399
2263005.42986382424533.8012612472263578.34454102424600.573958979
2263649.93152597 424581.02245348
#Sta/Elev= 30
       0 2366.21    49.6 2362.56   145.8 2358.72   159.6 2356.08   171.8 2349.44
   175.9  2349.2   200.3 2351.38   209.8 2350.93   216.7 2347.16   240.7 2328.89
   249.1 2324.39   257.2 2321.81   281.2 2320.11   395.5 2320.44   497.2  2318.2
   590.6 2319.61   735.5  2315.5   896.6 2318.96   904.7 2317.83   915.9 2313.42
   936.9 2312.06     978  2313.7   985.2 2311.94  1005.4 2311.75  1021.7 2313.34
  1037.6 2327.45  1046.5 2332.93  1152.5 2354.23  1195.9 2370.841226.721 2379.46
#Mann= 8 ,-1,0
       0     .05       0    49.6      .1       0   175.9    .016       0
   209.8      .1       0   281.2     .05       0   915.9      .1       0
     978    .045       0  1021.7      .1       0
#XS Ineff= 2 , 0
          337.35 2328.27
Permanent Ineff=
       F       F
Bank Sta=978,1021.7
XS Rating Curve= 0 ,0
Exp/Cntr(USF)=0,0
Exp/Cntr=0.3,0.1

Type RM Length L Ch R = 1 ,3078    ,421.8,651.9,571.6
XS GIS Cut Line= 4
2262537.66334874424501.9230675912263083.79813567424681.851195066
2263291.24468264424838.4945060452263488.10722211425073.459472513
#Sta/Elev= 30
       0  2362.5    40.5 2359.97    74.3 2352.78    99.5 2353.23   120.6 2342.54
     137 2337.33   162.7 2326.12   183.7 2320.54   204.8 2318.99   264.3    2320
   331.7 2318.26   554.3 2316.05   589.1  2315.1   607.1 2312.69   635.6 2316.43
   694.7 2317.77   838.5 2317.16   869.8 2315.07     880 2311.53   911.1 2310.91
   968.1 2311.49   979.5 2315.78  1019.2 2318.22  1035.7 2321.08  1052.4 2331.28
  1066.9 2341.76  1079.3 2353.25  1104.4 2370.02  1124.3 2377.11 1141.49  2379.7
#Mann= 9 ,-1,0
       0     .06       0    40.5      .1       0    74.3    .016       0
    99.5      .1       0   183.7     .05       0   331.7     .05       0
   635.6      .1       0     880    .045       0   968.1      .1       0
#XS Ineff= 2 , 0
          264.37 2330.15
Permanent Ineff=
       F       F
Bank Sta=880,968.1
XS Rating Curve= 0 ,0
Exp/Cntr(USF)=0,0
Exp/Cntr=0.3,0.1

Type RM Length L Ch R = 1 ,2426    ,256.2,252.3,268.6
XS GIS Cut Line= 4
2262514.89984448424638.3498747252262623.84748487424759.704062815
2262814.79144052424979.1144873062263077.68799943425195.463278147
#Sta/Elev= 30
       0 2365.96    13.9 2358.04    22.7 2355.74    34.1 2355.21    55.8 2356.91
    84.4 2357.33    99.2  2355.7   110.5 2352.27   127.4 2348.94   132.8 2346.87
   150.2 2336.33   181.9 2322.91   192.7 2320.16   209.7 2318.96   244.6 2318.19
   266.4 2317.68   280.6 2310.07   303.3 2310.02   329.4 2309.34   345.8 2310.79
     389  2314.8     428 2315.26   476.3 2313.62   507.5 2317.03   590.4 2318.02
     606  2322.8   668.1 2351.26     709 2365.97   756.2 2376.91   794.4 2378.85
#Mann= 8 ,-1,0
       0      .1       0    55.8    .016       0    99.2     .08       0
   110.5     .07       0   209.7     .05       0   244.6      .1       0
   303.3    .045       0   345.8      .1       0
#XS Ineff= 2 , 0
                           519.1         2329.85
Permanent Ineff=
       F       F
#Block Obstruct= 3 ,-1
   97.63  146.53 2376.34   477.3  515.81  2336.8  524.49  569.78 2337.47
Bank Sta=303.3,345.8
XS Rating Curve= 0 ,0
Exp/Cntr(USF)=0,0
Exp/Cntr=0.3,0.1

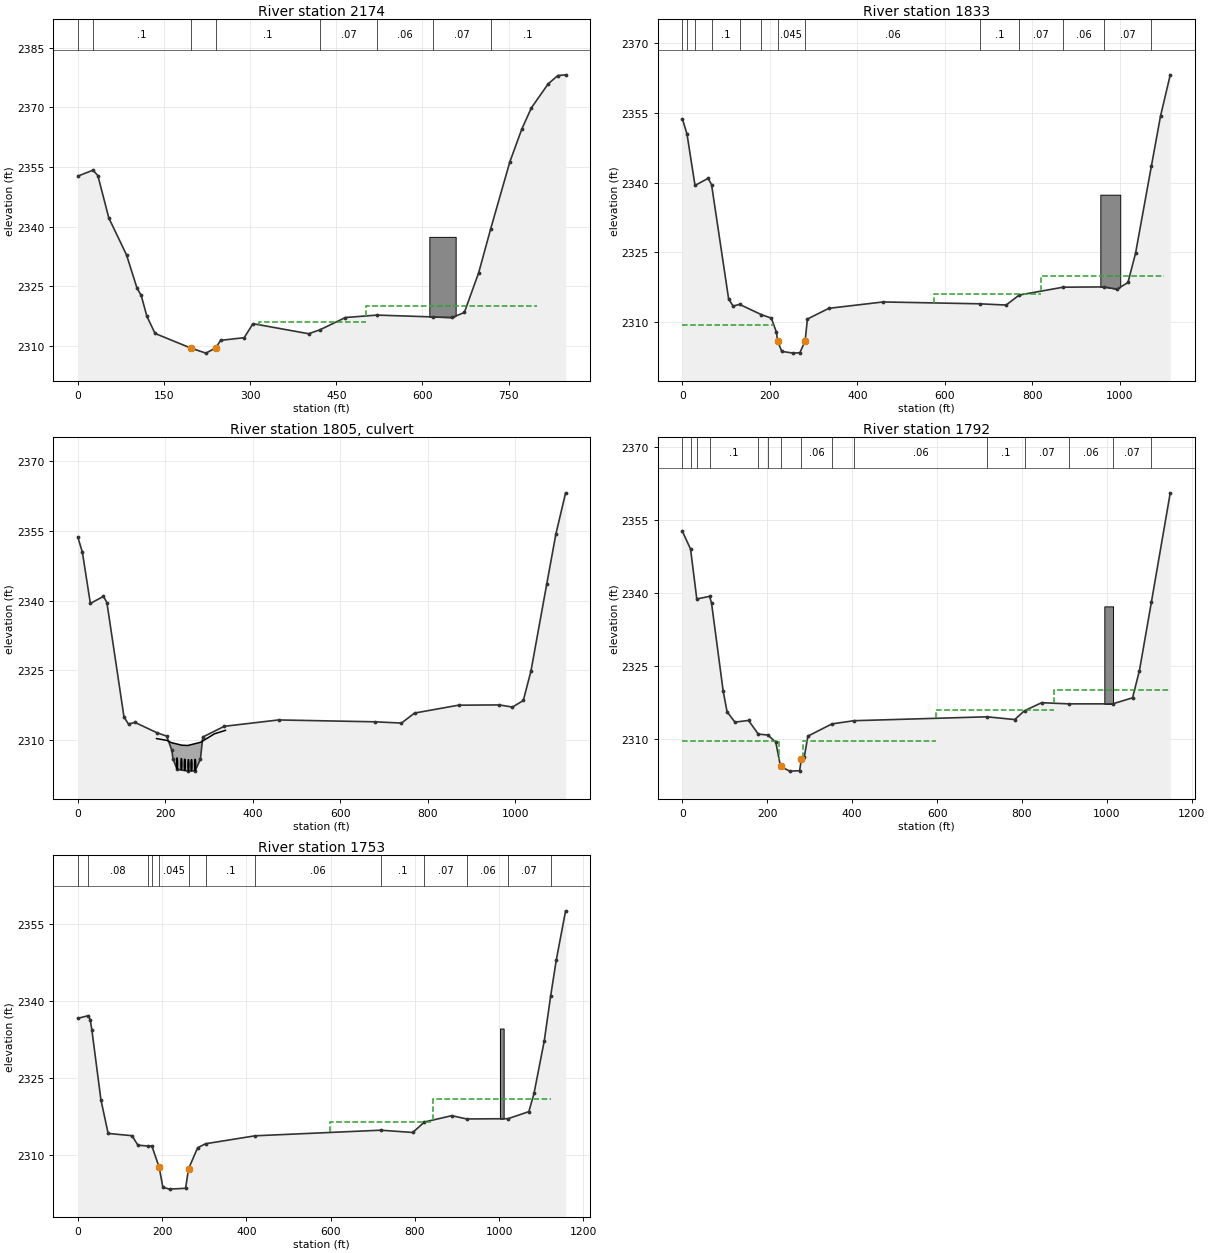
Type RM Length L Ch R = 1 ,2174    ,330.5,340.4,155.6
BEGIN DESCRIPTION:
structure xs 4
END DESCRIPTION:
XS GIS Cut Line= 5
2262369.35976371424830.9844965162262559.35218158425068.475018854
2262599.97940442425119.8938632172262828.69807547425126.488110188
2263069.33182955425197.219880963
#Sta/Elev= 30
       0 2352.72    26.3 2354.21    34.9 2352.87      54 2342.19    84.8 2332.91
   103.2 2324.48   110.4  2322.7   120.2 2317.48   134.5 2313.13   197.1 2309.43
   223.1 2308.18   239.8 2309.46   248.7 2311.39   289.7 2312.07     305 2315.59
   401.9 2313.06   421.7 2314.06   465.9 2317.14     521 2317.75   618.8 2317.29
   651.8 2317.15     673 2318.41     698 2328.43   718.8 2339.43   752.2  2356.3
     773 2364.55   789.7  2369.9   818.9 2375.93   835.6 2378.02   849.3 2378.21
#Mann= 8 ,-1,0
       0    .016       0    26.3      .1       0   197.1    .045       0
   239.8      .1       0   421.7     .07       0     521     .06       0
   618.8     .07       0   718.8      .1       0
#XS Ineff= 2 ,-1
     315     501    2316     501     800    2320
Permanent Ineff=
       F       F
#Block Obstruct= 1 ,-1
  612.04  657.85 2337.44
Bank Sta=197.1,239.8
XS Rating Curve= 0 ,0
Exp/Cntr(USF)=0,0
Exp/Cntr=0.5,0.3

Type RM Length L Ch R = 1 ,1833    ,39.3,41,23.7
BEGIN DESCRIPTION:
structure xs 3 - Channel burned based on survey DOU022CU
END DESCRIPTION:
XS GIS Cut Line= 6
2262062.76034392424907.1536476342262219.87460552425163.271416554
2262242.99404219 425206.936290472262515.41608292425137.266552783
2262825.51533116425140.2802851732262993.59458786425184.631442118
#Sta/Elev= 30
       0 2353.64    10.4 2350.42    28.7 2339.38    58.7  2340.9    66.5 2339.57
   105.6 2314.96   115.9 2313.45   130.5 2313.82   180.7  2311.6   203.2 2310.86
   214.8 2307.84   217.5 2305.99  226.91 2303.72  252.85 2303.34  268.33 2303.42
   280.32305.906   285.7 2310.67   334.7 2312.97     459 2314.34   679.3 2313.94
   739.9 2313.67   769.8 2315.82   870.3 2317.51   963.8 2317.57   993.6  2317.1
  1018.4 2318.52  1035.8 2324.81  1071.8 2343.45  1092.9  2354.3  1115.1 2363.15
#Mann= 13 ,-1,0
       0     .06       0    10.4      .1       0    28.7    .016       0
    66.5      .1       0   130.5     .06       0   180.7      .1       0
   217.5    .045       0   280.3     .06       0   679.3      .1       0
   769.8     .07       0   870.3     .06       0   963.8     .07       0
  1071.8      .1       0
#XS Ineff= 4 ,-1
       0     209 2309.46     285     575 2309.54     575     820    2316
     820    1100    2320
Permanent Ineff=
       F       F       F       F
#Block Obstruct= 1 ,-1
  955.28 1000.81 2337.39
Bank Sta=217.5,280.3
XS Rating Curve= 0 ,0
Exp/Cntr(USF)=0,0
Exp/Cntr=0.5,0.3

Type RM Length L Ch R = 2 ,1805    ,,,
BEGIN DESCRIPTION:
Twin Creeks Rd
Survey ID:54075DOU020RP
road deck from surveyed deck points
channel burned per surveyed invert points
6x2.5' CMP culverts
END DESCRIPTION:
Bridge Culvert--1,0,-1,-1, 0
Deck Dist Width WeirC Skew NumUp NumDn MinLoCord MaxHiCord MaxSubmerge Is_Ogee
15.72005,20,2.6,0, 8, 9, , , 0.98, 0, 0,0,,
     180  203.71   213.8  238.08  251.23   280.8  312.59  337.54
 2310.33 2309.94 2309.46 2308.91 2308.85 2309.54 2311.37  2312.1
                                                                
     180  203.71   213.8  238.08  251.23   280.8  312.59  337.54     345
 2310.33 2309.94 2309.46 2308.91 2308.85 2309.54 2311.37 2312.65  2312.5
                                                                        
BR Coef=-1 ,-1 , 0 ,, 0 ,,,0.8,0,,0,
WSPro=,,,, 1 ,,,, 0 ,,,, 0 ,,,,-1 ,-1 ,-1 , 0 , 0 , 0 , 0 , 0
Culvert=1,2.5,2.5,19,0.013,0.5,1,1,1,2303.72,226.89,2303.46,234.98,Culvert #1  , 0 ,14.5
  226.89  234.98
BC Culvert Barrel=1,Barrel 1,0
Culvert Bottom n=0.013
Culvert=1,2.5,2.5,19,0.013,0.5,1,1,1,2303.58,236.78,2303.4,244.94,Culvert #2  , 0 ,14.5
  236.78  244.94
BC Culvert Barrel=1,Barrel 2,0
Culvert Bottom n=0.013
Culvert=1,2.5,2.5,19,0.013,0.5,1,1,1,2303.44,244.53,2303.38,252.88,Culvert #3  , 0 ,14.5
  244.53  252.88
BC Culvert Barrel=1,Barrel 3,0
Culvert Bottom n=0.013
Culvert=1,2.5,2.5,19,0.013,0.5,1,1,1,2303.34,252.83,2303.39,260.59,Culvert #4  , 0 ,14.5
  252.83  260.59
BC Culvert Barrel=1,Barrel 4,0
Culvert Bottom n=0.013
Culvert=1,2.5,2.5,19,0.013,0.5,1,1,1,2303.36,259.87,2303.4,267.68,Culvert #5  , 0 ,14.5
  259.87  267.68
BC Culvert Barrel=1,Barrel 5,0
Culvert Bottom n=0.013
Culvert=1,2.5,2.5,19,0.013,0.5,1,1,1,2303.42,268.31,2303.47,276.02,Culvert #6  , 0 ,14.5
  268.31  276.02
BC Culvert Barrel=1,Barrel 6,0
Culvert Bottom n=0.013
BR U #Sta/Elev= 30
       0 2353.64    10.4 2350.42    28.7 2339.38    58.7  2340.9    66.5 2339.57
   105.6 2314.96   115.9 2313.45   130.5 2313.82   180.7  2311.6   203.2 2310.86
   214.8 2307.84   217.5 2305.99  226.91 2303.72  252.85 2303.34  268.33 2303.42
   280.32305.906   285.7 2310.67   334.7 2312.97     459 2314.34   679.3 2313.94
   739.9 2313.67   769.8 2315.82   870.3 2317.51   963.8 2317.57   993.6  2317.1
  1018.4 2318.52  1035.8 2324.81  1071.8 2343.45  1092.9  2354.3  1115.1 2363.15
BR U #Mann= 13
       0     .06    10.4      .1    28.7    .016    66.5      .1   130.5     .06
   180.7      .1   217.5     .04   280.3     .06   679.3      .1   769.8     .07
   870.3     .06   963.8     .07  1071.8      .1
BR D #Sta/Elev= 30
       0 2352.62    19.1 2349.01    33.8 2338.75    63.9 2339.29    68.5 2337.92
      96 2319.81   105.2 2315.56   123.6 2313.45   155.7 2313.79   178.7 2310.99
   201.2  2310.8     220 2309.31   231.1 2304.34  252.92 2303.38  276.06 2303.47
   280.2 2305.84   286.9 2306.19   295.6 2310.57   352.1 2313.08     404 2313.74
   717.3 2314.54   782.9 2313.98     806 2315.79   846.4 2317.44   910.7  2317.2
  1013.7  2317.2  1060.6 2318.45  1076.8 2324.05    1105 2338.12  1149.4 2360.56
BR D #Mann= 15
       0     .08    19.1      .1    33.8    .016    63.9      .1   178.7    .016
   201.2     .08   231.1     .04   280.2     .06   352.1      .1     404     .06
   717.3      .1     806     .07   910.7     .06  1013.7     .07    1105      .1
BC Design=,, 0 ,, 0 ,,,,,,
BC Use User HTab Curves=0
BC User HTab FreeFlow(D)= 0

Type RM Length L Ch R = 1 ,1792    ,42.6,39.7,13.4
BEGIN DESCRIPTION:
structure xs 2 - Channel burned based on survey DOU018CD
END DESCRIPTION:
XS GIS Cut Line= 6
2262029.81161887424913.5059793292262165.32366592425153.973435364
2262215.15282232425223.5747303322262517.32084307425141.701660607
2262651.77176783425142.1926172072262988.11690163425190.721332821
#Sta/Elev= 30
       0 2352.62    19.1 2349.01    33.8 2338.75    63.9 2339.29    68.5 2337.92
      96 2319.81   105.2 2315.56   123.6 2313.45   155.7 2313.79   178.7 2310.99
   201.2  2310.8     220 2309.31   231.1 2304.34  252.92 2303.38  276.06 2303.47
   280.2 2305.84   286.9 2306.19   295.6 2310.57   352.1 2313.08     404 2313.74
   717.3 2314.54   782.9 2313.98     806 2315.79   846.4 2317.44   910.7  2317.2
  1013.7  2317.2  1060.6 2318.45  1076.8 2324.05    1105 2338.12  1149.4 2360.56
#Mann= 15 ,-1,0
       0     .08       0    19.1      .1       0    33.8    .016       0
    63.9      .1       0   178.7    .016       0   201.2     .08       0
   231.1    .045       0   280.2     .06       0   352.1      .1       0
     404     .06       0   717.3      .1       0     806     .07       0
   910.7     .06       0  1013.7     .07       0    1105      .1       0
#XS Ineff= 4 ,-1
       0     228  2309.5     283     598  2309.5     598     875    2316
     875  1149.4    2320
Permanent Ineff=
       F       F       F       F
#Block Obstruct= 1 ,-1
  994.09 1014.65 2337.23
Bank Sta=231.1,280.2
XS Rating Curve= 0 ,0
Exp/Cntr(USF)=0,0
Exp/Cntr=0.5,0.3

Type RM Length L Ch R = 1 ,1753    ,47.8,49,15.8
BEGIN DESCRIPTION:
structure xs 4
channel burned 2.49' based on inverts from US structure
END DESCRIPTION:
XS GIS Cut Line= 6
2261999.09623352424960.1308153652262178.04765827425238.761428371
2262341.32810876425186.6678410842262519.23427806425144.640753724
 2262654.7456889425145.7667814642262986.04185163425204.528744237
#Sta/Elev= 30
       0 2336.62    24.8 2337.13    29.5 2336.36    33.5 2334.26    54.9 2320.73
      72 2314.19   128.5 2313.75   142.7  2311.9     167 2311.74   175.7 2311.75
   193.2 2307.58   201.9 2303.69   218.1 2303.34   255.8 2303.51   262.8  2307.3
   284.4  2311.4   303.1 2312.18   420.8 2313.73   718.7 2314.82     795 2314.38
   822.7 2316.42   887.5 2317.65   922.9 2317.01  1020.9 2317.06  1070.5 2318.44
  1082.7 2321.98  1107.1 2332.25  1122.2 2340.96  1135.5 2347.95  1157.7 2357.56
#Mann= 13 ,-1,0
       0    .016       0    24.8     .08       0     167    .016       0
   175.7     .08       0   193.2    .045       0   262.8     .06       0
   303.1      .1       0   420.8     .06       0   718.7      .1       0
   822.7     .07       0   922.9     .06       0  1020.9     .07       0
  1122.2      .1       0
#XS Ineff= 2 ,-1
  598.31  843.72 2316.51  843.72 1122.93 2320.95
Permanent Ineff=
       F       F
#Block Obstruct= 1 ,-1
    1002 1010.65 2334.63
Bank Sta=193.2,262.8
XS Rating Curve= 0 ,0
Exp/Cntr(USF)=0,0
Exp/Cntr=0.3,0.1