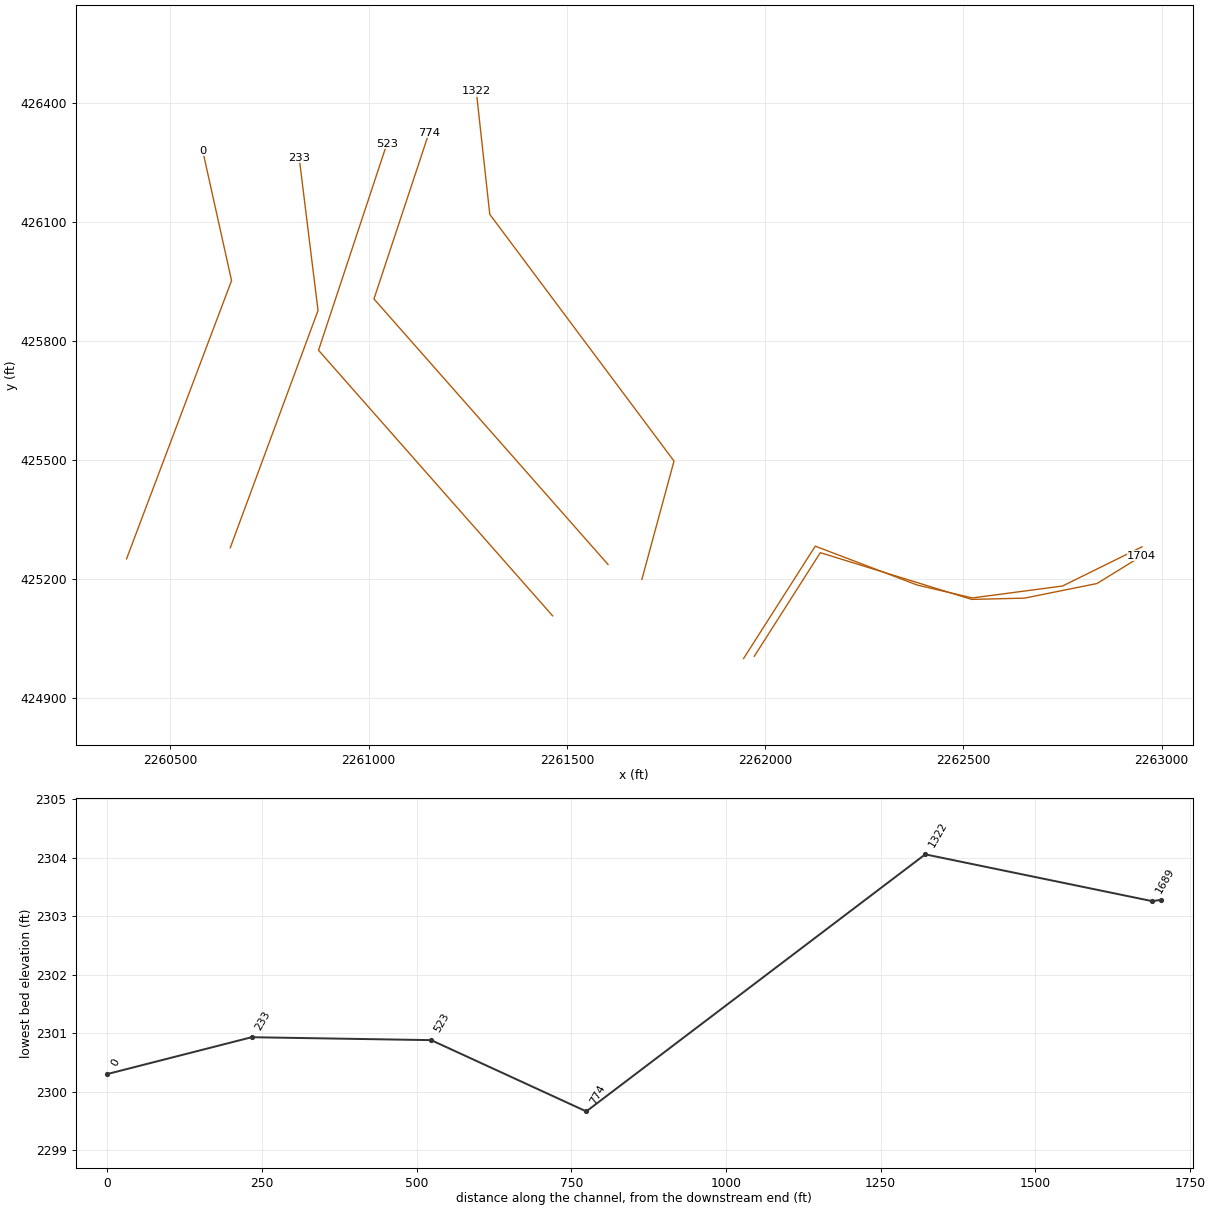
HEC-RAS study DOUTHTCK.prj: DOUTHTCK

--- DOUTHTCK.g01 (geometry) --- (continued)

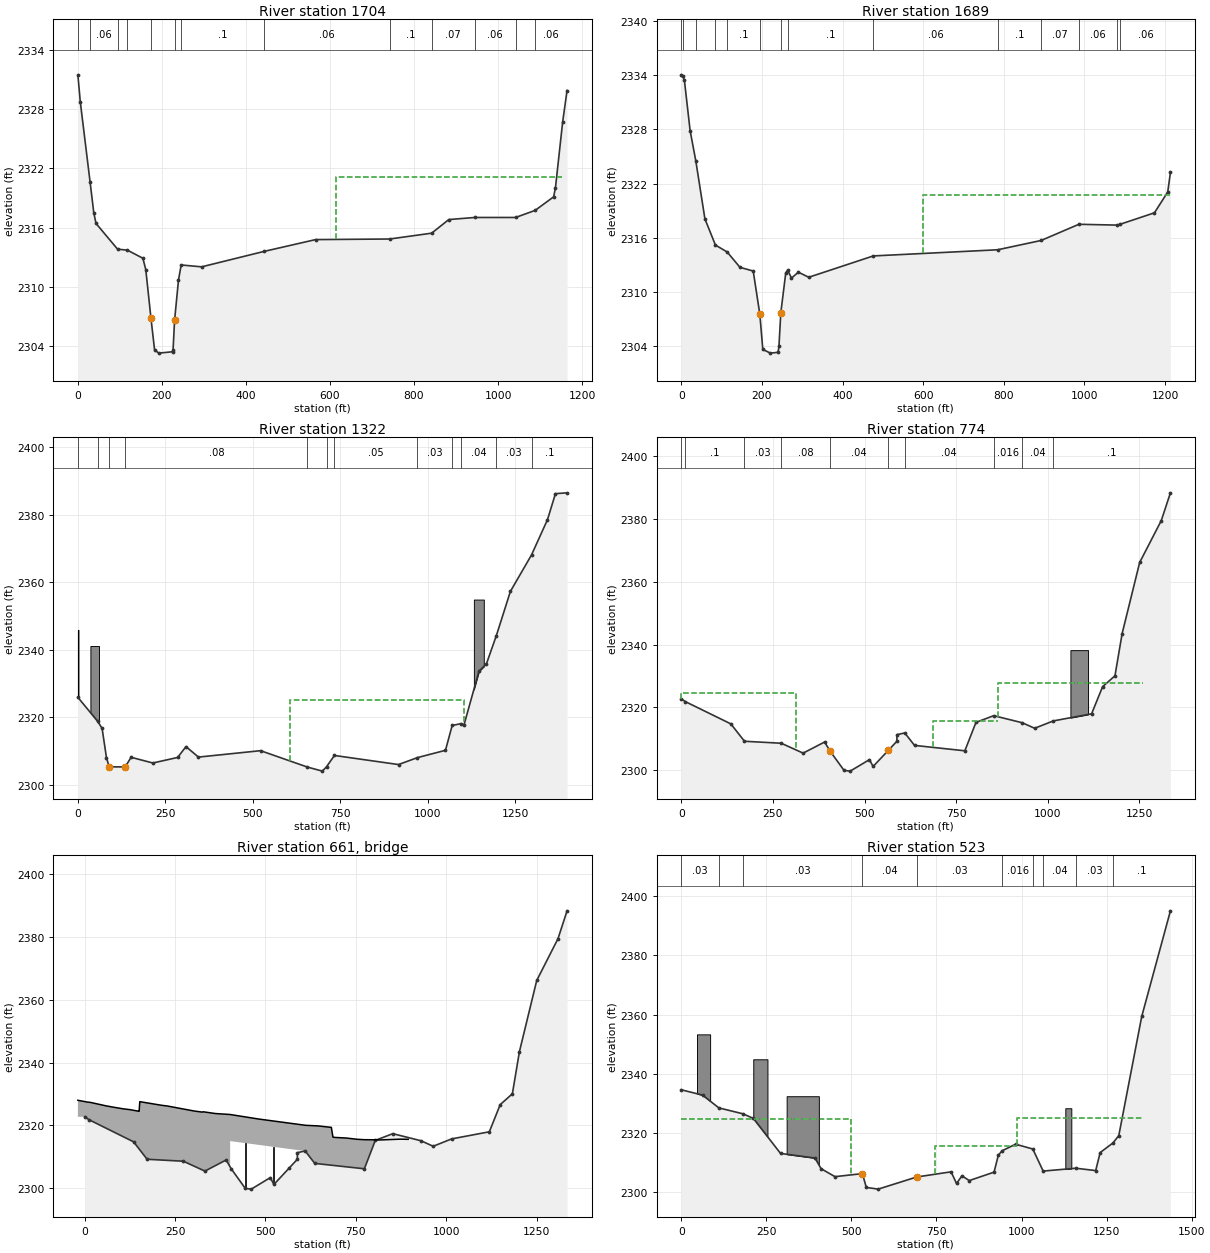
Type RM Length L Ch R = 1 ,1704    ,16.4,15,95.5
BEGIN DESCRIPTION:
structure xs 3
channel burned 2.50' based on inverts from US structure
Swinging bridge does not have any impact so no modeled
END DESCRIPTION:
XS GIS Cut Line= 6
2261972.61973172425004.2592791512262139.13446246425265.638719173
2262520.76802967425147.7757306982262653.93883235425150.879645347
2262837.04111727425187.794816694 2262949.7456085425257.466383025
#Sta/Elev= 30
       0 2331.47     5.7 2328.75    29.1  2320.6    37.8 2317.52    43.1 2316.42
    94.5 2313.81   117.9 2313.71   154.7 2312.89   161.6 2311.74     174 2306.79
  182.49 2303.62   192.5 2303.28   225.4 2303.42  226.53  2303.6   230.1 2306.59
   239.4 2310.67   245.8 2312.21   294.5 2312.02   443.7 2313.59   565.7 2314.78
   741.9 2314.84   841.9 2315.43   882.7 2316.81   944.3 2317.02  1041.6 2317.02
  1088.2 2317.74  1132.1 2319.11  1136.4 2319.99  1153.7 2326.72  1164.1 2329.88
#Mann= 13 ,-1,0
       0     .07       0    29.1     .06       0    94.5    .016       0
   117.9     .08       0     174    .045       0   230.1     .06       0
   245.8      .1       0   443.7     .06       0   741.9      .1       0
   841.9     .07       0   944.3     .06       0  1041.6     .07       0
  1088.2     .06       0
#XS Ineff= 3 ,-1
       0     123  2310.5     252     615  2310.5     615 1152.422321.151
Permanent Ineff=
       F       F       F
Bank Sta=174,230.1
XS Rating Curve= 0 ,0
Exp/Cntr(USF)=0,0
Exp/Cntr=0.3,0.1

Type RM Length L Ch R = 1 ,1689    ,353.4,366.5,605.6
BEGIN DESCRIPTION:
structure xs 2
channel burned 2.55' based on inverts from US structure
Swinging bridge does not have any impact so no modeled
END DESCRIPTION:
XS GIS Cut Line= 6
2261945.62080918424998.6345036212262126.44932678425282.013762863
 2262383.6100653425183.900577573 2262522.5901148425151.418369545
 2262750.0259739425181.5135905112262950.59185182425280.400212399
#Sta/Elev= 30
       0 2334.04     3.7 2333.93     7.8 2333.44      22 2327.87    36.2  2324.5
    58.7 2318.11    84.8 2315.21   113.8 2314.45   145.6 2312.75   178.5 2312.34
   194.9 2307.56   202.3 2303.67     221 2303.26   240.2 2303.35   242.3    2304
     247 2307.75   259.2 2312.13   263.9 2312.44   273.4 2311.56   290.5 2312.21
   316.2 2311.65   476.3 2314.01   784.6 2314.69   892.5 2315.72   986.2 2317.51
  1080.2 2317.42  1089.1 2317.52  1173.6 2318.78  1206.5 2321.08  1213.2 2323.24
#Mann= 14 ,-1,0
       0    .016       0     3.7      .1       0    36.2     .06       0
    84.8    .016       0   113.8      .1       0   194.9    .045       0
     247     .06       0   263.9      .1       0   476.3     .06       0
   784.6      .1       0   892.5     .07       0   986.2     .06       0
  1080.2      .1       0  1089.1     .06       0
#XS Ineff= 3 ,-1
       0     145 2309.25     270  600.23 2309.25  600.23 1213.212320.721
Permanent Ineff=
       F       F       F
Bank Sta=194.9,247
XS Rating Curve= 0 ,0
Exp/Cntr(USF)=0,0
Exp/Cntr=0.3,0.1

Type RM Length L Ch R = 1 ,1322    ,337.4,548,608.5
BEGIN DESCRIPTION:
structure xs 4
END DESCRIPTION:
XS GIS Cut Line= 4
 2261689.1251882425198.2677872672261770.11657157425496.657094395
2261305.48179332426119.0119349782261271.38015822426430.189355269
#Sta/Elev= 30
       0 2325.93    56.9 2318.77    69.3 2316.71    81.8 2308.03    89.6 2305.33
   135.3 2305.31   152.2 2308.16   214.4 2306.47   285.2 2308.11   309.2 2311.32
   344.8 2308.22   522.4 2310.12   656.5 2305.26   699.2 2304.06   711.1 2305.36
   733.7  2308.7   916.9 2306.01   971.2 2308.07  1051.2 2310.23  1070.4 2317.59
  1095.9 2318.14  1104.1 2317.71    1147 2333.68  1168.2 2335.82  1196.7 2344.21
  1236.9 2357.33  1297.3 2368.14  1342.9 2378.58  1365.7 2386.29  1398.9 2386.54
#Mann= 12 ,-1,0
       0     .03       0    56.9      .1       0    89.6    .045       0
   135.3     .08       0   656.5     .04       0   711.1     .08       0
   733.7     .05       0   971.2     .03       0  1070.4    .016       0
  1095.9     .04       0  1196.7     .03       0  1297.3      .1       0
#XS Ineff= 1 ,-1
  606.98 1104.65 2325.15
Permanent Ineff=
       F
#Block Obstruct= 3 ,-1
       0    1.77 2345.93   35.85   60.35 2341.14 1132.43  1160.8 2354.91
Bank Sta=89.6,135.3
XS Rating Curve= 0 ,0
Exp/Cntr=0.5,0.3

Type RM Length L Ch R = 1 ,774     ,304.7,250.8,397.2
BEGIN DESCRIPTION:
Structure XS 3 - channel burned within banks
END DESCRIPTION:
XS GIS Cut Line= 3
2261603.80715989425235.7582723552261013.37997517425905.599639815
2261152.19640877426324.825269286
#Sta/Elev= 30
       0 2322.71    11.5  2321.8   135.2 2314.73   172.5 2309.18   272.8 2308.55
   332.5  2305.4   391.1 2308.94   405.5 2306.12  444.17 2299.89  460.81 2299.66
  513.48 2303.33  523.38 2301.14  565.06  2306.3  588.28 2309.18   588.4 2311.28
   609.8 2311.83   636.4 2307.86   773.7 2306.14     804  2315.2   852.4 2317.34
   930.4 2315.08   964.1 2313.32  1015.1 2315.67  1119.5 2317.94  1149.5 2326.59
  1183.2 2330.05  1202.8 2343.53  1250.6 2366.18  1309.5 2379.52  1334.5 2388.38
#Mann= 10 ,-1,0
       0     .03       0    11.5      .1       0   172.5     .03       0
   272.8     .08       0   405.5     .04       0  565.06     .03       0
   609.8     .04       0   852.4    .016       0   930.4     .04       0
  1015.1      .1       0
#XS Ineff= 3 ,-1
       0     314  2324.7     686  865.24  2315.6  865.24 1259.61 2327.64
Permanent Ineff=
       F       F       F
#Block Obstruct= 1 ,-1
 1061.68 1109.81 2338.23
Bank Sta=405.5,565.06
XS Rating Curve= 0 ,0
Exp/Cntr=0.5,0.3

Type RM Length L Ch R = 3 ,661     ,,,
BEGIN DESCRIPTION:
Route 39/ Route 32
Bridge data: 54075KNA050
Width: 33' (measured on orthoimagery)
Railing height: 3.1
2 Rectangular Piers, each with width: 3'
Structure bounding sections incorporate channel data from survey.
Deck from Lidar with survey data incorporated.
END DESCRIPTION:
Bridge Culvert--1,0,-1,-1, 0
Deck Dist Width WeirC Skew NumUp NumDn MinLoCord MaxHiCord MaxSubmerge Is_Ogee
91,33,2.6,0, 30, 30, , , 0.98, 0, 0,0,,
     -19    7.79   15.45   58.07   79.38  106.99  126.26   149.5  150.48  152.33
  212.57  228.55  301.88  325.22   327.5  361.27  402.27  480.97  611.31  645.09
  682.33  686.72  692.05  722.58  753.71   773.2  805.58  812.98  872.21  894.92
 2327.98  2327.4 2327.31 2326.23 2325.78 2325.25 2324.98 2324.48 2324.47 2327.54
 2326.39 2326.16 2324.58 2324.21 2324.32 2323.76 2323.45 2322.01    2320 2319.82
 2319.34 2316.25 2316.14 2315.96 2315.55 2315.42 2315.39 2315.32 2315.58 2315.54
                                                                                
                                                 2314.98 2313.77 2311.78
                                                                                
     110  136.79  144.45  187.07  208.38  235.99  255.26   278.5  279.48  281.33
  341.57  357.55  430.88  454.22   456.5  490.27  531.27  609.97  740.31  774.09
  811.33  815.72  821.05  851.58  882.71   902.2  934.58  941.98 1001.21 1023.92
 2327.98  2327.4 2327.31 2326.23 2325.78 2325.25 2324.98 2324.48 2324.47 2327.54
 2326.39 2326.16 2324.58 2324.21 2324.32 2323.76 2323.45 2322.01    2320 2319.82
 2319.34 2316.25 2316.14 2315.96 2315.55 2315.42 2315.39 2315.32 2315.58 2315.54
                                                                                
                                                 2314.98 2313.77 2311.78
                                                                                
Pier Skew, UpSta & Num, DnSta & Num=  ,444.17, 2 ,565.62, 2 , 0 , 0 , 0 ,,
       3       3
 2299.89 2314.98
       3       3
 2301.16 2314.98
Pier Skew, UpSta & Num, DnSta & Num=  ,523.38, 2 ,645.94, 2 , 0 , 0 , 0 ,,
       3       3
 2301.14 2314.98
       3       3
 2301.75 2314.98
BR Coef=-1 ,-1 , 0 ,1.25, 0 ,,,0.8,0,2,0,
WSPro=,,,, 1 ,,,, 0 ,,,, 0 ,,,,-1 ,-1 ,-1 , 0 , 0 , 0 , 0 , 0
BR U #Sta/Elev= 30
       0 2322.71    11.5  2321.8   135.2 2314.73   172.5 2309.18   272.8 2308.55
   332.5  2305.4   391.1 2308.94   405.52306.116  444.17 2299.89  460.81 2299.66
  513.48 2303.33  523.38 2301.14  565.06  2306.3  588.28 2309.18   588.4 2311.28
   609.8 2311.83   636.4 2307.86   773.7 2306.14     804  2315.2   852.4 2317.34
   930.4 2315.08   964.1 2313.32  1015.1 2315.67  1119.5 2317.94  1149.5 2326.59
  1183.2 2330.05  1202.8 2343.53  1250.6 2366.18  1309.5 2379.52  1334.5 2388.38
BR U #Mann= 10
       0     .03    11.5      .1   172.5     .03   272.8     .08   405.5    .035
  565.06     .03   609.8     .04   852.4    .016   930.4     .04  1015.1      .1
BR D #Sta/Elev= 30
       0 2334.52    62.5 2332.73   110.5 2328.39   181.2 2326.39   211.8 2324.84
   291.8 2312.97     393 2311.41     411  2307.8   451.8  2305.1  532.36 2306.13
  543.84 2301.46  578.79 2300.88  692.02 2304.99     793 2306.74     809 2302.79
     825  2305.4   846.3 2303.77   919.3 2306.63   931.9  2312.4   943.3 2313.88
   982.5 2316.09  1033.1 2314.47  1063.6 2306.99  1159.5 2307.96    1218 2307.16
  1231.1 2313.26    1269 2316.54  1285.9 2319.03  1353.3 2359.36  1437.6 2395.12
BR D #Mann= 10
       0     .03   110.5     .04   181.2     .03  532.36    .035  692.02     .03
   943.3    .016  1033.1     .03  1063.6     .04  1159.5     .03    1269      .1
BC Design=,, 0 ,, 0 ,,,,,,
BC Use User HTab Curves=0
BC User HTab FreeFlow(D)= 0

Type RM Length L Ch R = 1 ,523     ,400.2,290.2,36.1
BEGIN DESCRIPTION:
Structure XS 2 - channel burned within banks
END DESCRIPTION:
XS GIS Cut Line= 3
2261463.96914245425106.2786265832260873.54195773425776.119994043
2261046.18148543426297.491367684
#Sta/Elev= 30
       0 2334.52    62.5 2332.73   110.5 2328.39   181.2 2326.39   211.8 2324.84
   291.8 2312.97     393 2311.41     411  2307.8   451.8  2305.1  532.36 2306.13
  543.84 2301.46  578.79 2300.88  692.02 2304.99     793 2306.74     809 2302.79
     825  2305.4   846.3 2303.77   919.3 2306.63   931.9  2312.4   943.3 2313.88
   982.5 2316.09  1033.1 2314.47  1063.6 2306.99  1159.5 2307.96    1218 2307.16
  1231.1 2313.26    1269 2316.54  1285.9 2319.03  1353.3 2359.36  1437.6 2395.12
#Mann= 10 ,-1,0
       0     .03       0   110.5     .04       0   181.2     .03       0
  532.36     .04       0  692.02     .03       0   943.3    .016       0
  1033.1     .03       0  1063.6     .04       0  1159.5     .03       0
    1269      .1       0
#XS Ineff= 3 ,-1
       0     500  2324.7     745  987.04  2315.6  987.04 1353.01    2325
Permanent Ineff=
       F       F       F
#Block Obstruct= 4 ,-1
   46.29   84.89 2353.29  211.66  253.36 2344.85  309.73   404.4 2332.34
 1128.67 1146.37 2328.27
Bank Sta=532.36,692.02
XS Rating Curve= 0 ,0
Exp/Cntr=0.5,0.3

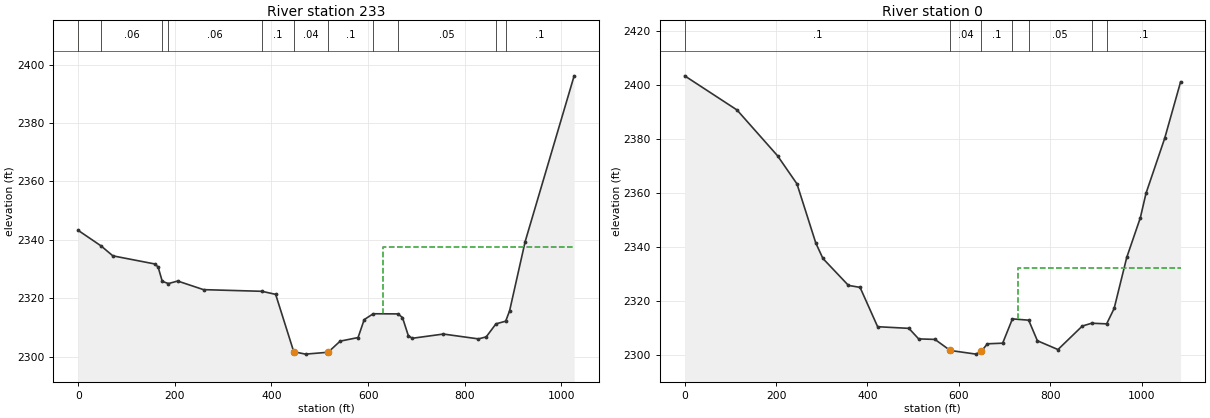
Type RM Length L Ch R = 1 ,233     ,232.1,233.2,231.6
BEGIN DESCRIPTION:
xs 1
END DESCRIPTION:
XS GIS Cut Line= 3
2260650.93809625425277.9382704612260872.30888103425876.459281157
2260824.75515689426261.808425029
#Sta/Elev= 30
       0 2343.26    47.1 2337.97    71.7 2334.55   159.2 2331.75   165.4  2330.7
     174 2325.82   186.8 2325.07   205.9 2325.93   259.3 2322.99   380.2 2322.42
   408.6 2321.38  446.07 2301.75   470.4 2300.93   517.2 2301.57   542.1 2305.37
   579.2  2306.6   591.9 2312.74   610.6 2314.74   661.8 2314.69   671.1 2313.44
   683.2 2307.25   691.3 2306.35   755.8  2307.8   828.3 2306.14   844.4 2306.83
   864.6 2311.29   884.7  2312.2   892.8 2315.75     925 2339.43  1026.4 2396.13
#Mann= 11 ,-1,0
       0      .1       0    47.1     .06       0     174    .016       0
   186.8     .06       0   380.2      .1       0  446.07     .04       0
   517.2      .1       0   610.6    .016       0   661.8     .05       0
   864.6    .016       0   884.7      .1       0
#XS Ineff= 2 , 0
                          630.08         2337.69
Permanent Ineff=
       F       F
Bank Sta=446.07,517.2
XS Rating Curve= 0 ,0
Exp/Cntr=0.3,0.1

Type RM Length L Ch R = 1 ,0       ,343.9,319,315.9
XS GIS Cut Line= 3
2260389.41498273425250.0739377682260654.21766343 425951.88932634
2260581.50243348426279.194746158
#Sta/Elev= 30
       0 2403.52  114.48 2390.86  203.21 2373.88  245.77 2363.44  287.02 2341.48
  302.59 2335.77  358.41 2325.79  383.82 2325.06  422.29 2310.47   490.7 2309.86
  512.07 2305.95  547.76 2305.76 581.0982301.661  637.78  2300.3 649.3982301.403
  662.61 2304.13  695.91 2304.36  717.29 2313.37   752.9 2312.89  771.92 2305.26
  816.99    2302  870.25 2310.72  890.75 2311.76  923.53 2311.53  939.92 2317.24
  967.47 2336.16  997.28  2350.9 1009.58 2359.91 1050.55 2380.35  1085.4 2401.31
#Mann= 7 ,-1,0
       0      .1       0 581.098     .04       0 649.398      .1       0
  717.29    .016       0   752.9     .05       0  890.75    .016       0
  923.53      .1       0
#XS Ineff= 2 , 0
                          728.79         2332.11
Permanent Ineff=
       F       F
Bank Sta=581.098,649.398
XS Rating Curve= 0 ,0
Exp/Cntr(USF)=0,0
Exp/Cntr=0.3,0.1
LCMann Table=0

Chan Stop Cuts=-1
Use User Specified Reach Order=0
Composite Channel Slope=5